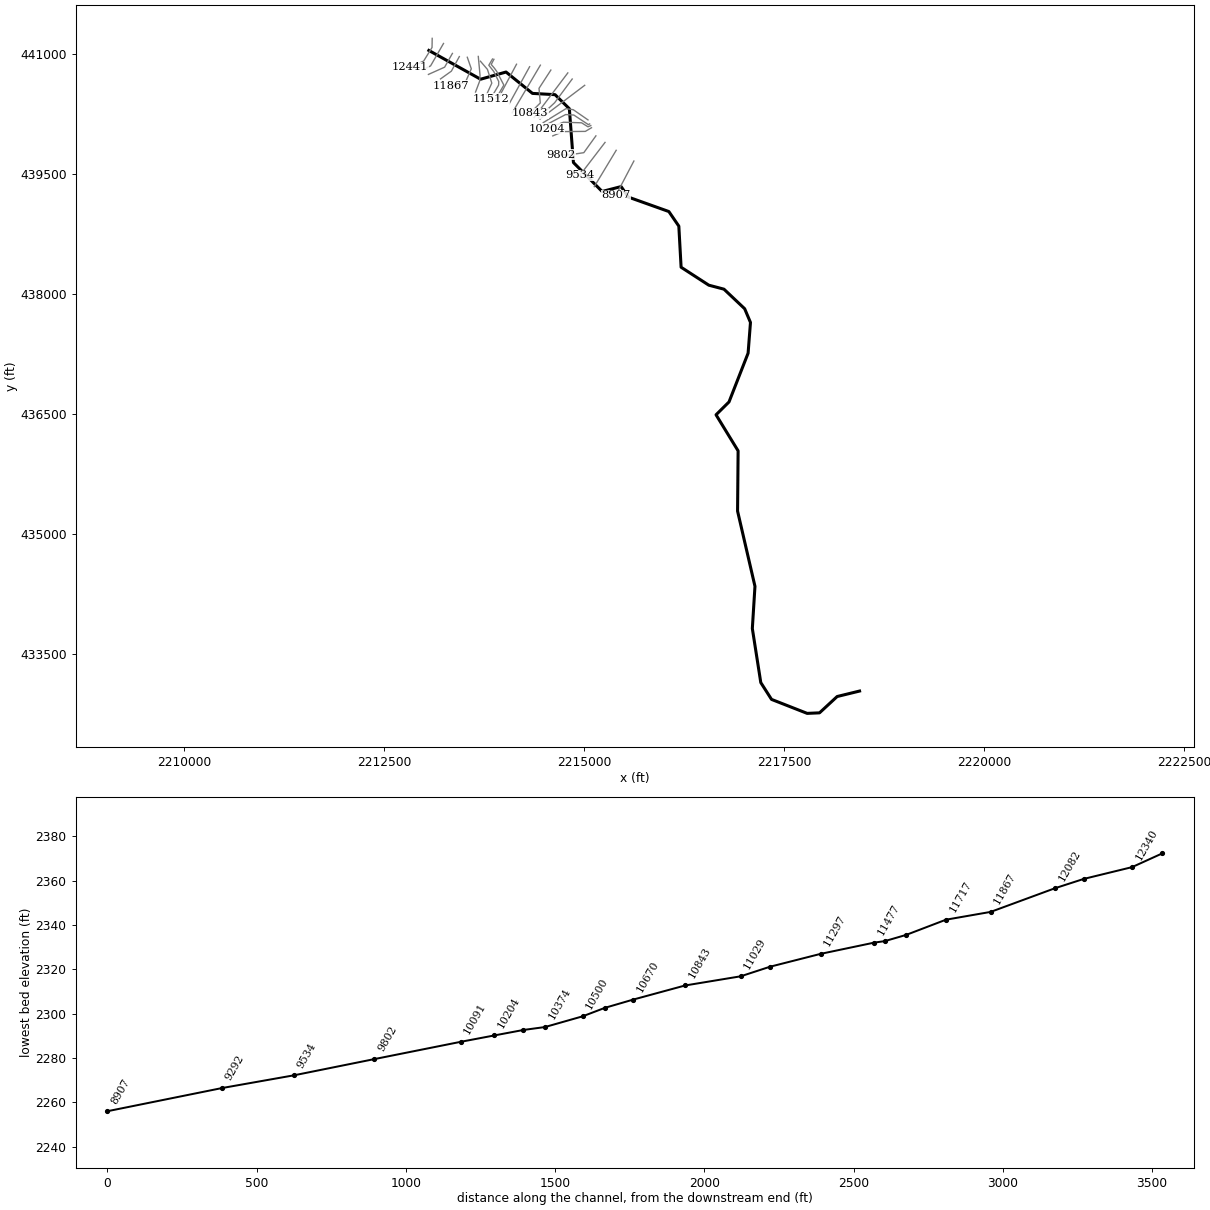
--- SWAGOCK.prj (project) ---

Proj Title=SWAGOCK
Current Plan=p01
Default Exp/Contr=0,0
English Units
Geom File=g01
Flow File=f01
Plan File=p01
Background Map Layer=Inundation Boundary (01pct Value_0)
Background Map Layer=Inundation Boundary (01pct Value_0)
BEGIN DESCRIPTION:
----------MODEL BY WOOD PLC 2021----------
Stream Name: Swago Creek
Flood Zone: Enhanced Approximate/ Detailed
Pocahontas County, WV
HEC-RAS Version: RAS 6.1
Vertical Datum: NAVD88
Projection: NAD 1983 StatePlane West Virginia S FIPS 4702 (US Feet)
Terrain: 1-meter LIDAR (FEMA Region III 3DEP collected 2016-2018)
Land Use: 2019 NLCD
Hydrologic Method:
WV SIR2010-5033 regression equations
Model Notes:
Upstream of RS 6002:  Enhanced Approximate
Downstream of RS 6002:  Detailed
Normal depth tie in to Greenbrier River
END DESCRIPTION:
DSS File=dss
DSS Export Rating Curves= 0
DSS Export Rating Curve Sorted= 0
DSS Export Volume Flow Curves= 0
DXF OffsetX= 0
DXF OffsetY= 0
DXF ScaleX= 0
DXF ScaleY= 0

--- SWAGOCK.p01 (plan) ---

Plan Title=Floodplain
Program Version=6.10
Short Identifier=Floodplain
Geom File=g01
Flow File=f01
Subcritical Flow
K Sum by GR= 0
Std Step Tol= 0.01
Critical Tol= 0.01
Num of Std Step Trials= 20
Max Error Tol= 0.3
Flow Tol Ratio= 0.001
Split Flow NTrial= 30
Split Flow Tol= 0.02
Split Flow Ratio= 0.02
Log Output Level= 0
Friction Slope Method= 1
Unsteady Friction Slope Method= 2
Unsteady Bridges Friction Slope Method= 1
Parabolic Critical Depth
Global Vel Dist= 0 , 0 , 0
Global Log Level= 0
CheckData=True
Encroach Param=-1 ,0,0, 2
Encroach River=SWAGOCK
Encroach Reach=Main
Encroach Node=6002
       1     175     240
Encroach Node=5744
       1     176   202.6
Encroach Node=5403
       1   187.2  243.91
Encroach Node=5001
       1   345.6  385.63
Encroach Node=4760
       1  287.06  319.06
Encroach Node=4626
       1     303  366.49
Encroach Node=4510
       1  272.51  343.05
Encroach Node=4325
       1   179.2   217.4
Encroach Node=4153
       1     172  228.26
Encroach Node=3911
       1     185  232.05
Encroach Node=3573
       1  166.01     230
Encroach Node=3321
       1  156.77   195.1
Encroach Node=3001
       1   181.7   213.9
Encroach Node=2702
       1  198.62   234.1
Encroach Node=2415
       1   258.6     309
Encroach Node=2144
       1   326.3   372.9
Encroach Node=1946
       1     261     405
Encroach Node=1813
       1  229.68     394
Encroach Node=1744
       1  203.93  387.63
Encroach Node=1683
       1     210     386
Encroach Node=1622
       1  163.76     323
Encroach Node=1538
       1     199     348
Encroach Node=1396
       1  239.76   382.2
Encroach Node=1081
       1     339     455
Encroach Node=916
       1     335  451.83
Encroach Node=600
       1     270   470.7
Encroach Node=381
       1   260.5  386.27
Encroach Node=118
       1  233.65  414.84
Computation Interval=0.1SEC
Output Interval=1SEC
Instantaneous Interval=Max Profile
Mapping Interval=1HOUR
Computation Time Step Use Courant=        0
Computation Time Step Use Time Series=    0
Computation Time Step Count To Double=0
Computation Time Step Max Doubling=0
Computation Time Step Max Halving=0
Computation Time Step Residence Courant=0
Run HTab= 0
Run UNet= 0
Run Sediment= 0
Run PostProcess= 0
Run WQNet= 0
Run RASMapper=-1
UNET Theta= 0
UNET Theta Warmup= 0
UNET ZTol= 0
UNET ZSATol= 0
UNET MxIter= 0
UNET Max Iter WO Improvement= 0
UNET MaxInSteps= 0
UNET DtIC= 0
UNET DtMin= 0
UNET MaxCRTS= 0
UNET WFStab= 0
UNET SFStab= 0
UNET WFX= 1
UNET SFX= 1
UNET Gravity=32.174
UNET 1D Methodology=Finite Difference
UNET DSS MLevel= 1
UNET Pardiso=0
UNET DZMax Abort= 0
UNET Use Existing IB Tables= 0
UNET Froude Reduction=False
UNET Froude Limit= 0
UNET Froude Power= 0
UNET D1 Cores= 0
UNET WindReference=Eulerian
UNET WindDragFormulation=Hsu (1988)
UNET D2 Coriolis=0
UNET D2 Cores= 0
UNET D2 Theta= 1
UNET D2 Theta Warmup= 1
UNET D2 Z Tol= 0.01
UNET D2 Volume Tol= 0.01
UNET D2 Max Iterations= 20
UNET D2 Equation= 0
UNET D2 RampUpFraction=0.1
UNET D2 TimeSlices= 1
UNET D2 Turbulence Formulation=Non-Conservative (original)
UNET D2 Eddy Viscosity=0.3
UNET D2 Transverse Eddy Viscosity=0.1
UNET D2 Smagorinsky Mixing=0
UNET D2 BCVolumeCheck=0
UNET D2 Cores=0
UNET D2 SolverType=PARDISO (Direct)
UNET D2 Minimum Iterations= 2147483647
UNET D2 Maximum Iterations= 2147483647
UNET D2 Restart Number= 10
UNET D2 Relaxation Coeff=1.3
UNET D2 SOR Precondition Iterations= 10
UNET D2 ILUT Maximum Fill= 8
UNET D2 ILUT Tolerance=1E-08
UNET D1D2 MaxIter= 0
UNET D1D2 ZTol=0.01
UNET D1D2 QTol=0.1
UNET D1D2 MinQTol=1
DSS File=dss
Write IC File= 0
Write IC File at Fixed DateTime=0
Write IC File at Sim End=0
Echo Input=False
Echo Parameters=False
Echo Output=False
Write Detailed= 0
HDF Write Warmup=0
HDF Write Time Slices=0
HDF Flush=0
HDF Compression= 1
HDF Chunk Size= 1
HDF Spatial Parts= 1
HDF Use Max Rows=0
HDF Fixed Rows= 1
Calibration Method= 0
Calibration Iterations= 20
Calibration Max Change=0.05
Calibration Tolerance=0.2
Calibration Maximum=1.5
Calibration Minimum=0.5
Calibration Optimization Method= 1
WQ AD Non Conservative
WQ ULTIMATE=-1
WQ Max Comp Step=1HOUR
WQ Output Interval=15MIN
WQ Output Selected Increments= 0
WQ Output face flow=0
WQ Output face velocity=0
WQ Output face area=0
WQ Output face dispersion=0
WQ Output cell volume=0
WQ Output cell surface area=0
WQ Output cell continuity=0
WQ Output cumulative cell continuity=0
WQ Output face conc=0
WQ Output face dconc_dx=0
WQ Output face courant=0
WQ Output face peclet=0
WQ Output face adv mass=0
WQ Output face disp mass=0
WQ Output cell mass=0
WQ Output cell source sink temp=0
WQ Output nsm pathways=0
WQ Output nsm derived pathways=0
WQ Create Restart=0
WQ Fixed Restart=0
WQ System Summary=0
WQ Write To DSS=0
Sorting and Armoring Iterations= 10
XS Update Threshold= 0.02
Bed Roughness Predictor= 0
Hydraulics Update Threshold= 0.02
Energy Slope Method= 1
Volume Change Method= 1
Sediment Retention Method= 0
Sediment TS Multiplier= 1
Warm Up Method= 0
XS Weighting Method= 0
Number of US Weighted Cross Sections= 1
Number of DS Weighted Cross Sections= 1
Upstream XS Weight=0
Main XS Weight=1
Downstream XS Weight=0
Number of DS XS's Weighted with US Boundary= 1
Upstream Boundary Weight= 1
Weight of XSs Associated with US Boundary= 0
Number of US XS's Weighted with DS Boundary= 1
Downstream Boundary Weight= 0.5
Weight of XSs Associated with DS Boundary= 0.5
Percentile Method= 0
Sediment Output Level= 3
Mass or Volume Output= 0
Output Increment Type= 1
Profile and TS Output Increment= 1
Transport Output Increment 1
XS Output Flag= 0
XS Output Increment= 10
Read HDF5 Sediment Hotstart= 0
Sediment Hotstart Type= 0
Write Gradation File= 0
Read Gradation Hotstart= 0
Write HDF5 File= 1
Write Binary Output= 1
Write DSS Sediment File= 0
DSS Sediment Output Type= 1
SV Curve= 0
Specific Gage Flag= 0
Subcell Erosion Methods= 0
Subcell Deposition Methods= 0
Advection Scheme= 1
Matrix Solver= 0
Implicit Weighting Factor= 1
Maximum Outer Loop Convergence Iterations= 5
Convergence Maximum Absolute= 0.001
Convergence RMSE= 0.0001
Grain Fractions Max Abs Error= 0.001
Max Subgrid Regions= 1
Max Subgrid Length Scale= 3.402823E+38
Initial Layer Thickness= 3.402823E+38
Min Layer Thickness= 3.402823E+38
Max Layer Thickness= 3.402823E+38
Number of Layers= 5

--- SWAGOCK.f01 (steady flow) ---

Flow Title=Flow
Program Version=6.10
Number of Profiles= 7
Profile Names=01pct,FWY,10pct,04pct,02pct,0_2pct,01plus
River Rch & RM=SWAGOCK,Main            ,12441
     767     767     410     542     651    1070    1130
River Rch & RM=SWAGOCK,Main            ,11717
     862     862     463     611     732    1190    1270
River Rch & RM=SWAGOCK,Main            ,6429
    1480    1480     813    1060    1270    2030    2190
River Rch & RM=SWAGOCK,Main            ,6260
    1840    1840    1020    1320    1570    2510    2720
River Rch & RM=SWAGOCK,Main            ,5744
    2330    2330    1300    1680    1990    3160    3440
Boundary for River Rch & Prof#=SWAGOCK,Main            , 1
Up Type= 0
Dn Type= 3
Dn Slope=0.01113
Boundary for River Rch & Prof#=SWAGOCK,Main            , 2
Up Type= 0
Dn Type= 3
Dn Slope=0.01113
Boundary for River Rch & Prof#=SWAGOCK,Main            , 3
Up Type= 0
Dn Type= 3
Dn Slope=0.01113
Boundary for River Rch & Prof#=SWAGOCK,Main            , 4
Up Type= 0
Dn Type= 3
Dn Slope=0.01113
Boundary for River Rch & Prof#=SWAGOCK,Main            , 5
Up Type= 0
Dn Type= 3
Dn Slope=0.01113
Boundary for River Rch & Prof#=SWAGOCK,Main            , 6
Up Type= 0
Dn Type= 3
Dn Slope=0.01113
DSS Import GetInterval= 0
DSS Import GetPeak= 0
DSS Import FillOption= 0

--- SWAGOCK.g01 (geometry) ---

Geom Title=Geometry
Program Version=6.10

River Reach=SWAGOCK         ,Main
Reach XY= 30
     2213057.375      441042.8012213704.14809381440683.000642367
2214022.31540951440773.0214567122214353.14190223440505.772164126
2214635.30089219440490.018521616 2214814.2172607440314.196618598
2214865.06027599439641.4579525072215223.85784281439279.336947262
     2215461.745      439340.615     2215552.282      439209.079
2216058.38032965439028.5221816412216183.11928318438845.971439536
     2216211.514      438332.0372216557.94028086 438107.71899849
2216747.56745923438057.707434965     2217006.206      437813.317
     2217079.016      437641.497       2217049.3      437257.442
     2216810.524      436647.538     2216648.457      436486.866
     2216924.397      436036.005     2216917.662      435282.565
      2217135.21      434342.125     2217102.302      433814.521
     2217207.992      433138.434     2217342.256      432928.059
     2217787.817      432753.287     2217942.358      432759.929
     2218162.925      432964.029     2218443.316      433032.491

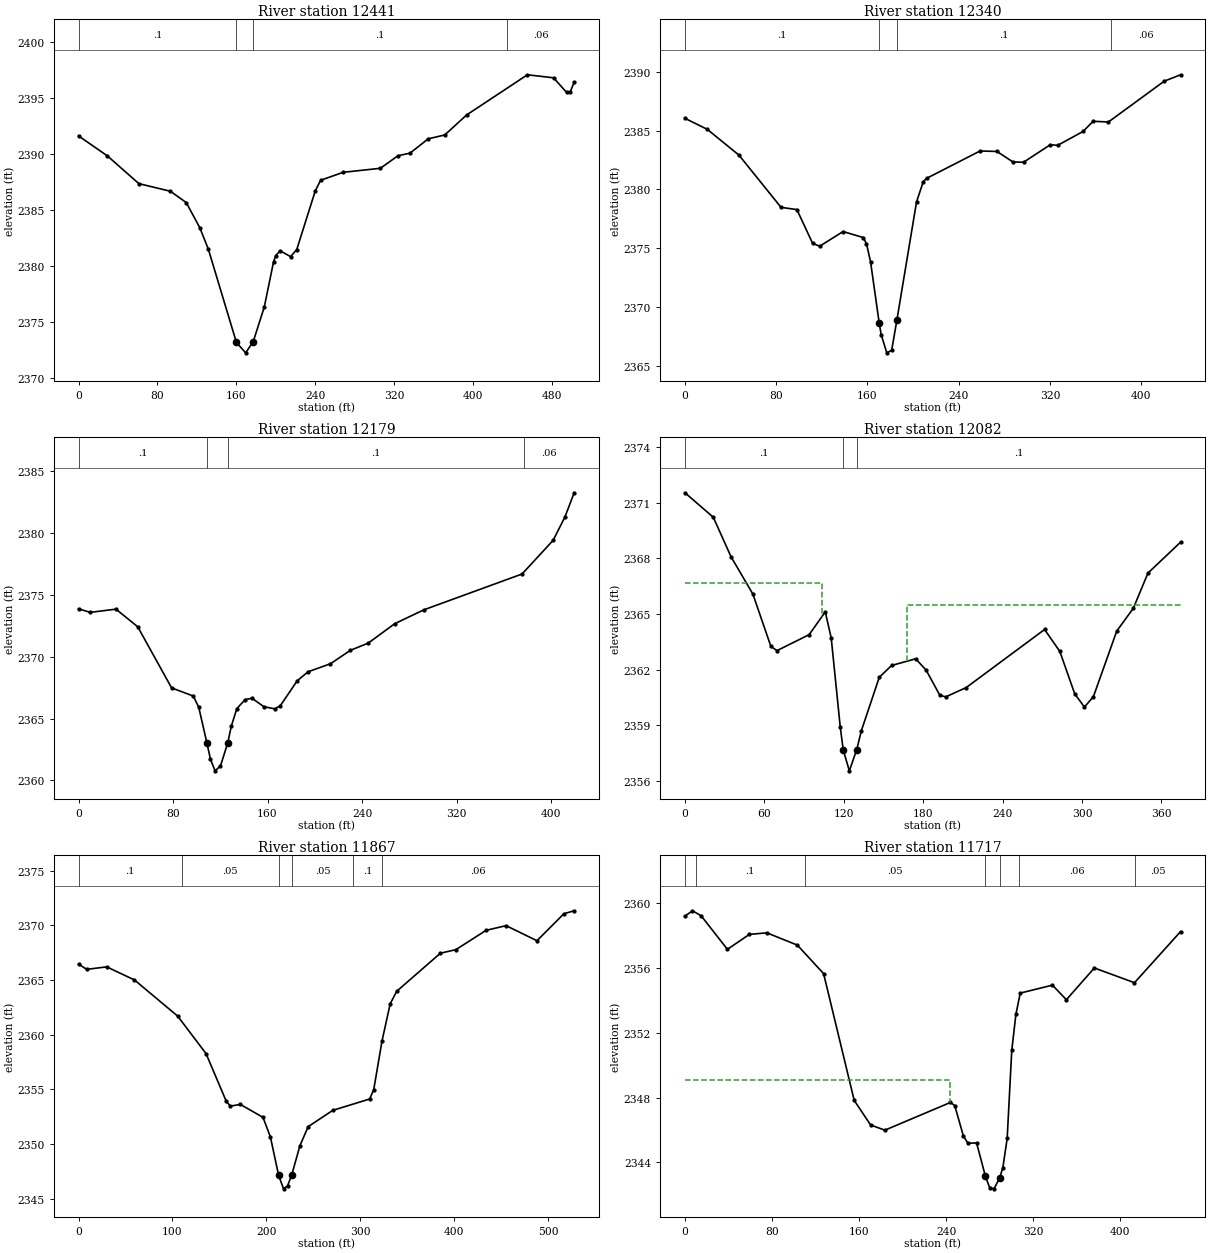
Type RM Length L Ch R = 1 ,12441   ,101.3,101.3,101.3
XS GIS Cut Line= 4
2213099.11051171441194.3530071832213097.13679915441079.882805205
2212991.97048387 440910.158949852212821.20537787440831.023900728
#Sta/Elev= 30
       0 2391.63    29.2 2389.85    61.2 2387.37    93.2 2386.69   109.2 2385.68
     123 2383.43   131.5 2381.55160.05192373.209   169.4 2372.28   177.1 2373.28
   188.3 2376.37   197.7  2380.4   199.9 2380.94   204.3 2381.39     215 2380.86
   221.2 2381.49     240 2386.73   245.4 2387.67   268.2 2388.38     306 2388.74
   323.8 2389.86     336 2390.09   354.5 2391.37   371.2 2391.71   393.3 2393.49
     455 2397.08   481.5 2396.81   494.7 2395.51   498.5 2395.57   502.4 2396.42
#Mann= 4 ,-1,0
       0      .1       0160.0519    .045       0   177.1      .1       0
  434.15     .06       0
Bank Sta=160.0519,177.1
XS Rating Curve= 0 ,0
Exp/Cntr(USF)=0,0
Exp/Cntr=0.3,0.1

Type RM Length L Ch R = 1 ,12340   ,161.3,161.4,161.4
XS GIS Cut Line= 3
2213240.51656861441130.1526063612213078.78880882 440849.67369427
2212979.26403356440801.042269997
#Sta/Elev= 30
       0 2386.05    19.6 2385.11    47.3 2382.92    84.2 2378.47    98.1 2378.28
   111.9  2375.4   118.1 2375.16   138.6 2376.41   156.2  2375.9   159.1 2375.38
   162.7 2373.82   170.22368.656     172 2367.63   176.9 2366.08   181.2  2366.3
   185.8 2368.89     203 2378.94   208.9 2380.66   211.8 2380.94   258.7 2383.27
   273.5 2383.23   287.4 2382.34   296.8 2382.31   320.2  2383.8   326.7 2383.75
   348.9 2384.93   357.8  2385.8   371.2 2385.74   420.2 2389.22   434.5 2389.76
#Mann= 4 ,-1,0
       0      .1       0   170.2    .045       0   185.8      .1       0
  373.77     .06       0
Bank Sta=170.2,185.8
XS Rating Curve= 0 ,0
Exp/Cntr(USF)=0,0
Exp/Cntr=0.3,0.1

Type RM Length L Ch R = 1 ,12179   ,96.9,97.1,97.3
XS GIS Cut Line= 3
2213351.78868241 441005.803385792213254.61037109440833.850699085
2213051.94010648440743.052105155
#Sta/Elev= 30
       0 2373.87     9.9 2373.58    31.7 2373.84    50.1 2372.42    78.8 2367.48
    97.2 2366.82   101.8 2365.91108.7861 2362.99   111.7 2361.72   115.6 2360.78
   120.2 2361.18126.38612363.054   129.3 2364.37     134  2365.8   141.1 2366.54
     147 2366.64   156.9 2365.96   166.1 2365.79   170.7 2366.02   185.1 2368.05
   194.3 2368.78   213.3 2369.43   230.1 2370.51   245.3  2371.1   267.6 2372.66
   292.2 2373.78   375.5 2376.68   401.8  2379.4   411.8 2381.29   419.6 2383.24
#Mann= 4 ,-1,0
       0      .1       0108.7861    .045       0126.3861      .1       0
  377.51     .06       0
Bank Sta=108.7861,126.3861
XS Rating Curve= 0 ,0
Exp/Cntr(USF)=0,0
Exp/Cntr=0.3,0.1

Type RM Length L Ch R = 1 ,12082   ,213.6,215,215.6
XS GIS Cut Line= 3
2213438.43515577440966.1629198562213338.91038052440784.077819668
2213203.19477789440686.814971121
#Sta/Elev= 30
       0 2371.54    21.4 2370.22    34.8 2368.09    51.3 2366.08    64.9 2363.26
    69.5 2363.03    93.8 2363.89     106 2365.12   110.5 2363.71   117.3 2358.92
   119.6 2357.67   124.2 2356.55   129.8  2357.7   133.3 2358.72   146.8 2361.59
   156.1 2362.23   174.3 2362.59   182.2 2361.98   192.6 2360.62   197.1 2360.54
   212.5 2361.04   271.7 2364.17   283.2 2362.99   294.5  2360.7   301.8 2359.99
   308.6 2360.55   326.2 2364.08   338.8 2365.32   349.8 2367.21   374.5 2368.88
#Mann= 3 ,-1,0
       0      .1       0   119.6    .045       0   129.8      .1       0
#XS Ineff= 2 , 0
          103.44 2366.69  168.11         2365.48
Permanent Ineff=
       F       F
Bank Sta=119.6,129.8
XS Rating Curve= 0 ,0
Exp/Cntr(USF)=0,0
Exp/Cntr=0.3,0.1

Type RM Length L Ch R = 1 ,11867   ,145.8,149.8,153.6
XS GIS Cut Line= 4
2213538.11244527440957.4938025612213588.12560813440813.305543921
2213513.39904329 440642.835728092213329.68821133440598.479647273
#Sta/Elev= 30
       0 2366.45     8.8 2365.97      30  2366.2    59.6    2365   105.6 2361.69
   135.8 2358.26   157.1 2353.94   161.5 2353.46   172.4 2353.61   196.4 2352.43
   204.3 2350.64213.07862347.114   218.3 2345.89   222.6 2346.17     227 2347.16
   235.7 2349.83   244.5 2351.58   270.7 2353.07     310 2354.11   314.3 2354.96
   323.1 2359.41   331.8 2362.81   338.7 2363.96   385.3 2367.45   401.7 2367.77
   433.9 2369.54   455.2 2369.97   488.1 2368.59   516.8 2371.06   527.7 2371.33
#Mann= 6 ,-1,0
       0      .1       0     110     .05       0213.0786    .045       0
     227     .05       0  292.62      .1       0  322.62     .06       0
Bank Sta=213.0786,227
XS Rating Curve= 0 ,0
Exp/Cntr(USF)=0,0
Exp/Cntr=0.3,0.1

Type RM Length L Ch R = 1 ,11717   ,128.8,133.1,137
XS GIS Cut Line= 4
2213675.40145459440968.0536402562213697.31447865440732.202718339
2213691.43658828440655.7901434572213641.16591523 440523.03784037
#Sta/Elev= 30
       0  2359.2     6.9 2359.53    14.9 2359.22      39 2357.15    59.1 2358.07
    75.2 2358.17   103.3 2357.41   127.4 2355.65   155.5 2347.83   170.6 2346.31
   183.7 2345.99   243.9  2347.7   247.9 2347.51   255.9 2345.62     260 2345.19
     268  2345.2     276 2343.17     280 2342.44     284 2342.37   289.2 2343.05
   292.1 2343.67   296.1 2345.48   300.3 2350.91   304.1 2353.13   308.1 2354.45
   337.7 2354.94   350.5 2354.04   376.2    2356   413.1 2355.09   455.5 2358.25
#Mann= 7 ,-1,0
       0     .06       0      10      .1       0     110     .05       0
     276    .045       0   289.2     .05       0  306.87     .06       0
  413.51     .05       0
#XS Ineff= 2 , 0
          243.94 2349.11
Permanent Ineff=
       F       F
Bank Sta=276,289.2
XS Rating Curve= 0 ,0
Exp/Cntr(USF)=0,0
Exp/Cntr=0.3,0.1

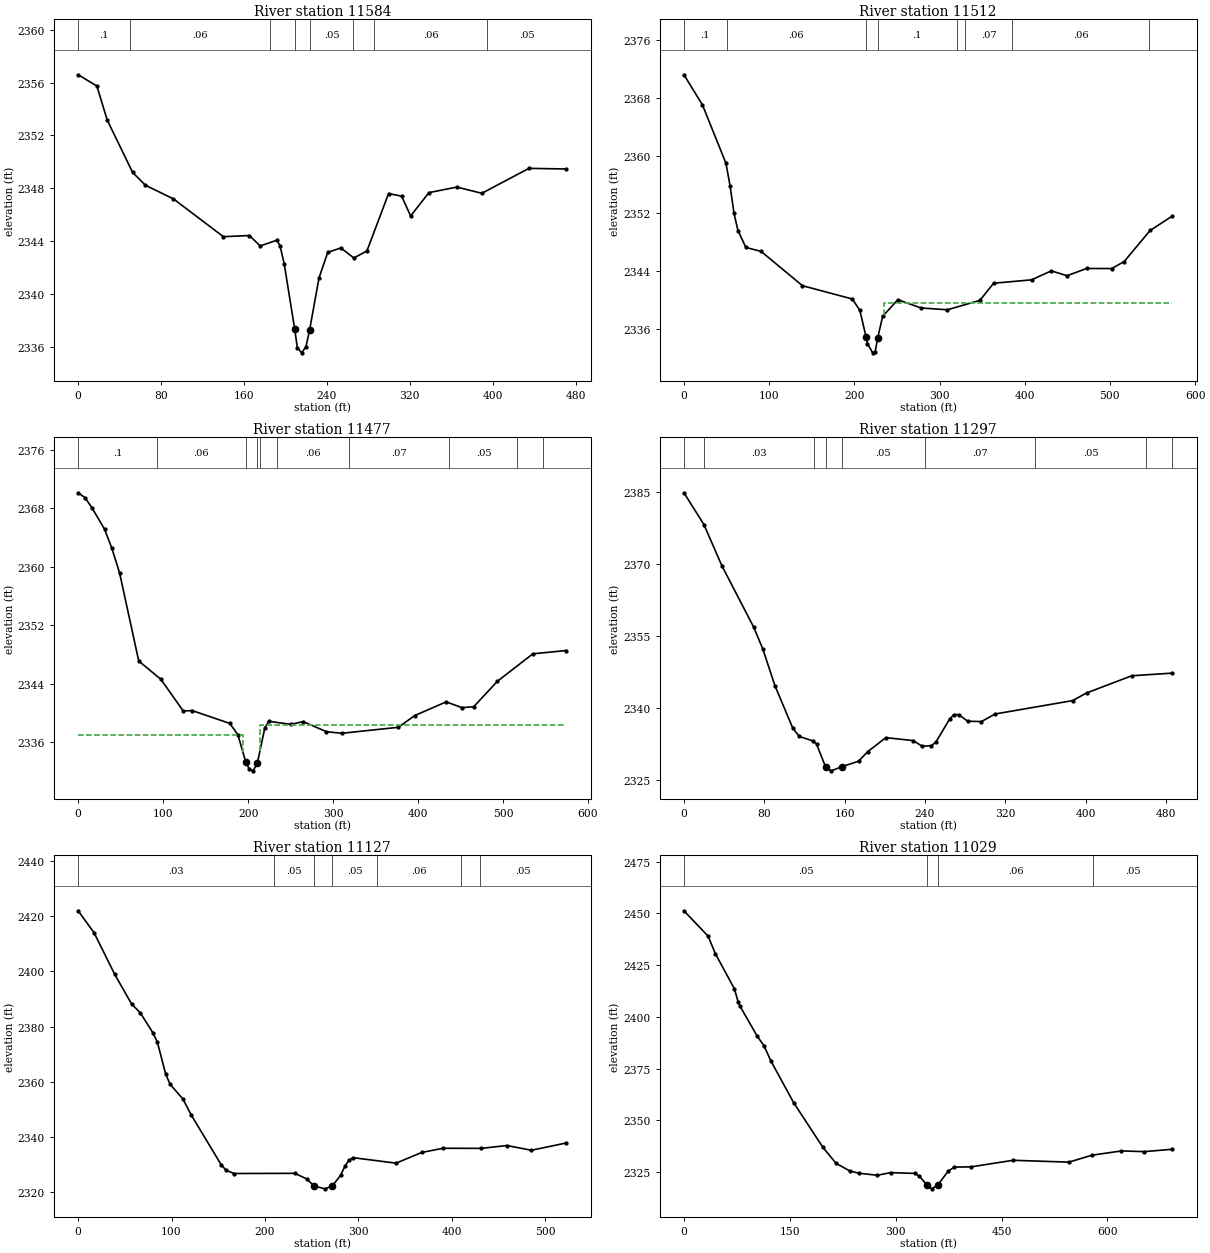
Type RM Length L Ch R = 1 ,11584   ,70,71.6,73.6
BEGIN DESCRIPTION:
Structure XS 4
END DESCRIPTION:
XS GIS Cut Line= 4
2213701.94961754440908.4837887412213790.16475924440805.566123417
2213844.45100029440634.7906567822213779.98608904440492.289274026
#Sta/Elev= 30
       0 2356.59    18.1 2355.74      28 2353.17    52.6 2349.19    64.9 2348.22
    91.9 2347.19   140.2 2344.32   165.3 2344.41   175.7 2343.62   191.6 2344.05
   194.8 2343.65   198.9 2342.25     2092337.316   211.5 2335.92   215.7 2335.52
   219.9 2335.99   223.4 2337.26   232.5 2341.21   240.9 2343.13   253.5 2343.47
   266.1 2342.71   278.7 2343.24   299.6 2347.59   312.2 2347.39   320.9 2345.89
   338.5 2347.66   365.5 2348.08   389.6 2347.61   435.1  2349.5   471.2 2349.45
#Mann= 8 ,-1,0
       0      .1       0      50     .06       0  185.55     .05       0
     209    .045       0   223.4     .05       0  265.55      .1       0
  285.55     .06       0  394.75     .05       0
Bank Sta=209,223.4
XS Rating Curve= 0 ,0
Exp/Cntr(USF)=0,0
Exp/Cntr=0.5,0.3

Type RM Length L Ch R = 1 ,11512   ,34.5,35,35.2
BEGIN DESCRIPTION:
Structure XS 3; 8.7 ft between structure and xs
END DESCRIPTION:
XS GIS Cut Line= 6
2213852.95334829440935.8792050942213807.10867101440857.859731176
2213868.86545787 440779.76517002 2213931.2757557440653.637552421
 2213929.4995024440609.2487275592213829.28164434440438.856417648
#Sta/Elev= 30
       0 2371.18    21.7 2367.02    49.3 2358.94    54.2 2355.79    58.8 2351.99
    63.4 2349.63    72.7 2347.29    90.5 2346.75   139.1    2342   197.6 2340.16
   206.5 2338.59  213.872334.858   215.4    2334   221.5 2332.71   224.4 2332.82
   227.5 2334.82   233.3 2337.77   251.1 2340.06   278.2 2338.92   309.2 2338.67
   347.4 2339.97   363.5 2342.34     408 2342.81   431.2 2344.05   449.7 2343.38
   472.7 2344.38   502.1 2344.37   516.7 2345.34   547.2 2349.64   573.1 2351.62
#Mann= 8 ,-1,0
       0      .1       0      50     .06       0  213.87    .045       0
   227.5      .1       0  320.24     .06       0  330.24     .07       0
  385.39     .06       0  545.39      .1       0
#XS Ineff= 2 , 0
             205  2338.4     235          2339.6
Permanent Ineff=
       F       F
Bank Sta=213.87,227.5
XS Rating Curve= 0 ,0
Exp/Cntr(USF)=0,0
Exp/Cntr=0.5,0.3

Type RM Length L Ch R = 1 ,11477   ,191,180.1,167.9
BEGIN DESCRIPTION:
Structure XS 2; 10.2 ft between structure and xs
END DESCRIPTION:
XS GIS Cut Line= 6
 2213870.9913376440932.3127334072213837.17017572440867.989151243
2213876.30858548440822.2177010312213906.11558327440780.745436478
2213995.24379267440609.6033217042213895.02593461440439.211011793
#Sta/Elev= 30
       0 2370.11     8.1 2369.44    16.3 2368.05    31.1 2365.12    39.7  2362.5
    48.7 2359.17    71.3 2347.09    97.4 2344.57   123.7 2340.24   134.2  2340.3
   178.5 2338.54     188 2336.99   197.3 2333.25   201.6 2332.25   205.9 2332.05
   210.92333.094   219.7 2337.92   224.3 2338.83   250.2 2338.42     265 2338.78
   292.2 2337.41   310.1 2337.19   376.9 2338.01     396 2339.61   433.1 2341.49
   451.7  2340.7   465.6 2340.83   493.4 2344.31   535.2 2348.07   574.6 2348.52
#Mann= 10 ,-1,0
       0      .1       0   92.67     .06       0   197.3    .045       0
   210.9     .06       0  213.97      .1       0  233.97     .06       0
  318.34     .07       0  436.94     .05       0  516.94     .06       0
  546.94      .1       0
#XS Ineff= 2 , 0
             194    2337     214          2338.3
Permanent Ineff=
       F       F
Bank Sta=197.3,210.9
XS Rating Curve= 0 ,0
Exp/Cntr(USF)=0,0
Exp/Cntr=0.5,0.3

Type RM Length L Ch R = 1 ,11297   ,168.4,169.7,169.5
BEGIN DESCRIPTION:
Structure XS 1
END DESCRIPTION:
XS GIS Cut Line= 2
2214153.54840605 440870.531432932213924.30874625440441.655910461
#Sta/Elev= 30
       0 2384.81    19.9  2378.2    37.8 2369.62    69.6  2356.8    78.6 2352.28
    90.7 2344.64   108.4 2335.84   114.9 2334.12   128.5 2333.18   132.1  2332.5
   141.12327.785   146.7 2326.96     1572327.805   173.9 2328.96     183 2330.94
   201.1 2333.87   228.3 2333.25   237.4 2332.06   246.5 2332.21     251 2332.95
   264.6 2337.73   269.1 2338.68   273.7 2338.64   282.7 2337.28   296.3 2337.21
     310 2338.79   387.1 2341.57     401 2343.16     446 2346.74   486.3 2347.29
#Mann= 9 ,-1,0
       0     .05       0      20     .03       0     130     .05       0
   141.1    .045       0     157     .05       0     240     .07       0
     350     .05       0     460     .06       0   486.3      .1       0
Bank Sta=141.1,157
XS Rating Curve= 0 ,0
Exp/Cntr(USF)=0,0
Exp/Cntr=0.3,0.1

Type RM Length L Ch R = 1 ,11127   ,98.6,98,97.6
XS GIS Cut Line= 2
2214317.19368277440839.4950240732214064.98885456440381.454865216
#Sta/Elev= 30
       0 2421.96    17.2 2413.92    39.2 2398.88    57.4 2388.08    66.6 2384.97
    80.3 2377.58    84.9 2374.29    93.7 2362.82    98.5 2359.05   112.2 2353.71
   121.4 2347.76   153.3 2329.83   158.5 2327.87     167 2326.71   232.2 2326.77
   244.7 2324.75   252.8 2322.17   264.5 2321.15   272.1 2322.16   281.2 2326.09
   285.8 2329.45   290.3 2331.64   294.9 2332.43   340.5 2330.46   367.9 2334.33
   390.8 2335.86   431.9 2335.82   459.3 2336.86   485.4 2335.13   522.9 2337.79
#Mann= 7 ,-1,0
       0     .03       0     210     .05       0   252.8    .045       0
   272.1     .05       0     320     .06       0     410     .08       0
     430     .05       0
Bank Sta=252.8,272.1
XS Rating Curve= 0 ,0
Exp/Cntr(USF)=0,0
Exp/Cntr=0.3,0.1

Type RM Length L Ch R = 1 ,11029   ,177.2,186.5,192.4
XS GIS Cut Line= 2
2214451.69088653440858.7274664292214099.55888771440263.261611523
#Sta/Elev= 30
       0 2451.23    34.3 2438.93    44.6 2430.43    71.5 2413.53    76.7 2407.31
    79.6 2405.03     104 2390.53   113.3 2386.08   123.4 2378.53   155.5 2358.45
     197 2336.85   215.6 2329.14   234.8 2325.53   248.1 2324.37   274.1 2323.41
   292.8 2324.67   327.1  2324.3   333.7 2322.93   344.8  2318.5   351.2 2316.84
   359.6 2318.71   374.6 2325.46   383.3 2327.35   406.7 2327.46   466.5 2330.64
   545.5 2329.74     578  2333.1   619.9 2335.16   652.4 2334.83   691.8 2335.97
#Mann= 4 ,-1,0
       0     .05       0   344.8    .045       0   359.6     .06       0
     580     .05       0
Bank Sta=344.8,359.6
XS Rating Curve= 0 ,0
Exp/Cntr(USF)=0,0
Exp/Cntr=0.3,0.1

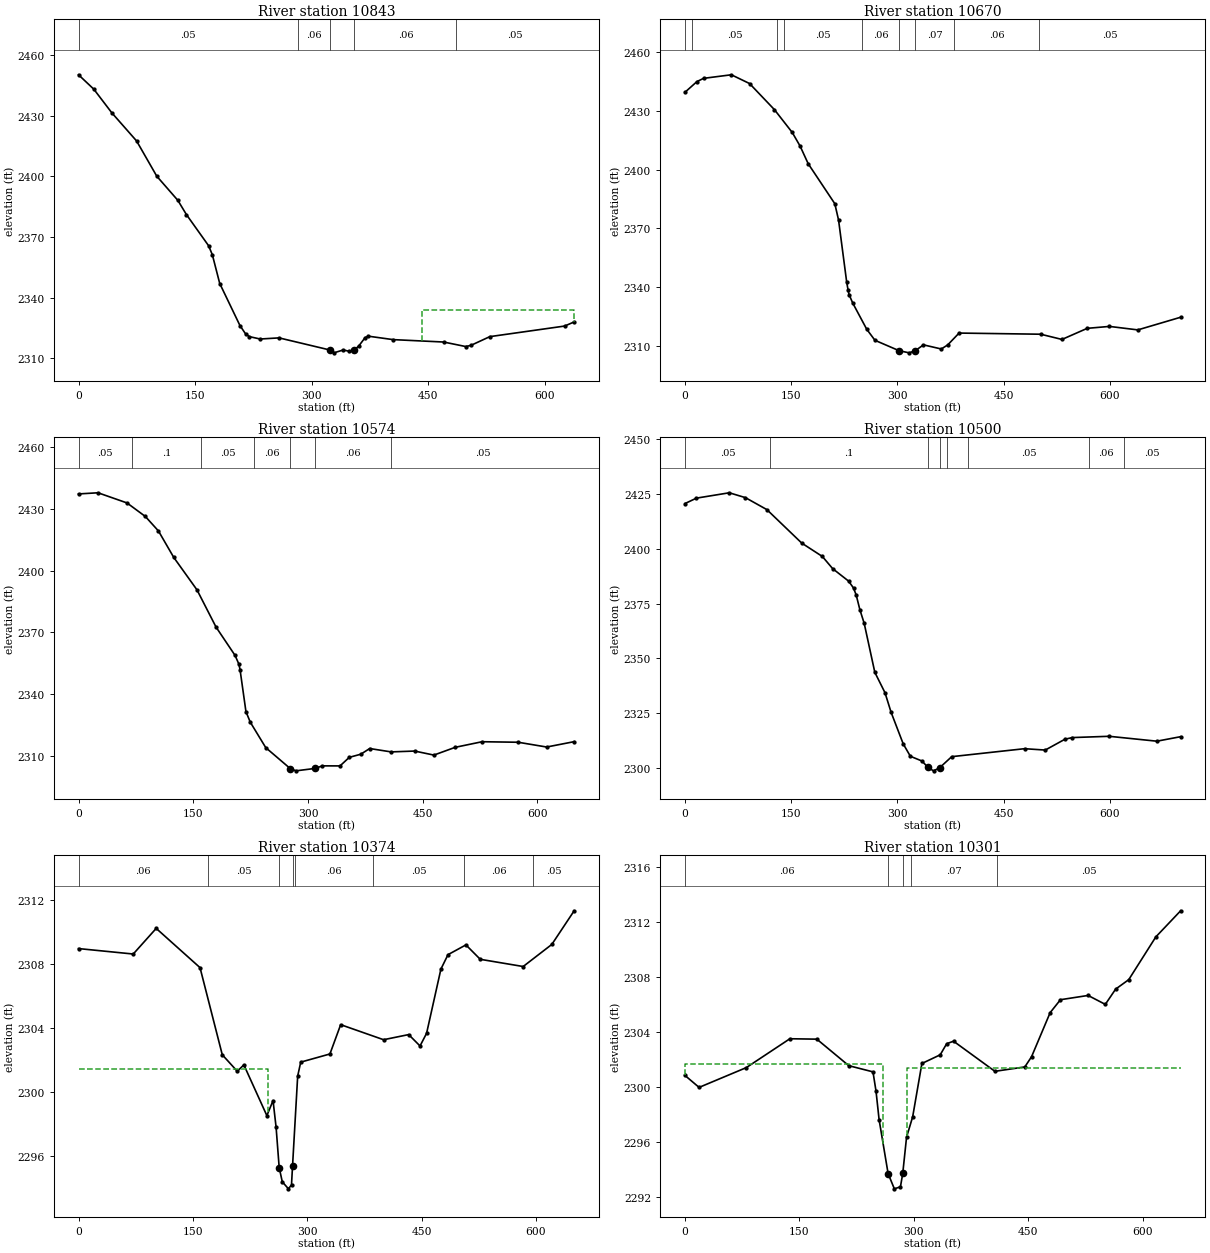
Type RM Length L Ch R = 1 ,10843   ,188,173.2,158.8
XS GIS Cut Line= 4
2214582.97007124440797.6493799312214434.81387171 440569.19478218
2214450.64735868440385.9787186372214321.71753619440258.179859499
#Sta/Elev= 30
       0 2450.29    19.7 2443.15    42.8 2431.49    74.7 2417.55   100.7  2400.1
   127.8 2388.15   138.8 2381.13   167.4 2365.68   172.2 2361.21   181.7    2347
   207.7  2326.2   215.1 2321.98   219.9 2320.71   233.7 2319.53     258 2320.09
  322.94 2314.14   328.5 2312.69   340.6  2314.1   348.6 2313.44   354.9 2314.12
   360.6  2316.1   368.7  2320.2   372.7 2320.94   404.8 2319.23   469.8 2318.04
   498.1 2315.81   504.7 2316.36   529.2 2320.71   625.4 2325.94   637.7 2327.99
#Mann= 5 ,-1,0
       0     .05       0  282.29     .06       0  322.94    .045       0
   354.9     .06       0  486.19     .05       0
#XS Ineff= 2 , 0
                          442.08         2334.06
Permanent Ineff=
       F       F
Bank Sta=322.94,354.9
XS Rating Curve= 0 ,0
Exp/Cntr(USF)=0,0
Exp/Cntr=0.3,0.1

Type RM Length L Ch R = 1 ,10670   ,93.4,95.3,94.4
XS GIS Cut Line= 2
2214795.00795009 440762.082959012214373.22429608440203.425148535
#Sta/Elev= 30
       0 2439.59    16.9 2445.05    26.2  2446.7    65.5 2448.53    91.2 2444.05
   126.4 2430.67   151.5 2419.03   162.6 2412.06     174 2403.06   211.6 2382.61
   216.9 2374.25   228.3 2342.73   230.4 2338.33   231.7 2336.16     237 2331.75
   256.7  2318.4   268.3 2312.76   302.5 2307.43   316.7 2306.35   325.4 2307.48
   336.8 2310.43     362 2308.32   371.1 2310.42   387.1 2316.46   502.4 2315.87
   532.4  2313.2   568.1 2318.88   599.5 2319.86   639.5 2318.08     700 2324.55
#Mann= 9 ,-1,0
       0      .1       0      10     .05       0     130      .1       0
     140     .05       0     250     .06       0   302.5    .045       0
   325.4     .07       0     380     .06       0     500     .05       0
Bank Sta=302.5,325.4
XS Rating Curve= 0 ,0
Exp/Cntr(USF)=0,0
Exp/Cntr=0.3,0.1

Type RM Length L Ch R = 1 ,10574   ,80.4,74.4,70.1
XS GIS Cut Line= 3
2214849.87742307440685.6840077662214630.47053216440389.371608703
2214425.76616487440199.369765028
#Sta/Elev= 30
       0 2437.27    25.5 2437.83    63.4 2432.89    87.4  2426.3   104.5 2419.26
   124.5 2406.41   154.9 2390.61   179.8 2372.52   204.7 2358.72   209.7 2354.47
   211.2 2351.78   218.9  2331.4   224.6 2326.25   244.8 2313.89  276.75 2303.74
   284.3 2302.61   309.2 2303.78   318.8 2305.03   341.9 2305.01     354 2309.17
     369 2310.69   380.7 2313.46   408.7 2311.82   439.5 2312.23   464.6 2310.27
   492.5 2314.05   527.7 2316.77   574.8 2316.51     612 2314.19     648  2316.8
#Mann= 7 ,-1,0
       0     .05       0      70      .1       0     160     .05       0
     230     .06       0  276.75    .045       0   309.2     .06       0
   408.7     .05       0
Bank Sta=276.75,309.2
XS Rating Curve= 0 ,0
Exp/Cntr(USF)=0,0
Exp/Cntr=0.3,0.1

Type RM Length L Ch R = 1 ,10500   ,137,126.4,114.8
BEGIN DESCRIPTION:
Structure XS 4
END DESCRIPTION:
XS GIS Cut Line= 2
2215006.08848329 440606.945620012214447.61992513440184.911415777
#Sta/Elev= 30
       0 2420.59    16.2 2423.06    62.6  2425.5    85.4 2423.28   115.7 2417.82
   164.9 2402.57     194 2396.48   208.6 2390.92   231.1 2385.24     238  2382.1
   241.8 2378.92     247 2372.22   253.1 2366.01   268.1 2343.69   282.5 2334.37
   291.1 2325.46   308.2 2311.08   318.3 2305.43   334.7 2303.26   343.3 2300.32
     351 2298.79   359.6 2300.18   376.7 2305.25   479.5 2308.88   508.8 2308.26
   536.6 2313.19     547 2313.95     599 2314.53   666.4  2312.3     700 2314.35
#Mann= 8 ,-1,0
       0     .05       0     120      .1       0   343.3    .045       0
   359.6      .1       0     370     .06       0     400     .05       0
     570     .06       0     620     .05       0
Bank Sta=343.3,359.6
XS Rating Curve= 0 ,0
Exp/Cntr(USF)=0,0
Exp/Cntr=0.5,0.3

Type RM Length L Ch R = 1 ,10374   ,71.9,72.3,74.6
BEGIN DESCRIPTION:
Structure XS 3; 14.4 ft between structure and xs
END DESCRIPTION:
XS GIS Cut Line= 4
  2215047.232719440174.4517970352214863.15697601440301.886713876
2214771.89066612440314.9060362742214487.15798967440139.976450981
#Sta/Elev= 30
       0 2308.94    71.8  2308.6   101.9  2310.2   159.4 2307.75   188.6 2302.31
   208.3 2301.28   216.9 2301.68   247.1 2298.51   255.2 2299.45   259.2 2297.78
263.23672295.268   267.3 2294.38   275.4 2293.94   279.4 2294.19280.73672295.339
   287.5 2300.98   291.5 2301.85   329.8 2302.36   343.9 2304.19   400.2 2303.25
   433.1 2303.57     448 2302.86   456.6 2303.65   475.4 2307.66   484.7 2308.56
   508.2 2309.17     527 2308.27   583.3 2307.82   620.9  2309.2   650.2  2311.3
#Mann= 8 ,-1,0
       0     .06       0     170     .05       0263.2367    .045       0
280.7367     .05       0  283.88     .06       0  386.07     .05       0
  506.07     .06       0  596.07     .05       0
#XS Ineff= 2 , 0
             249  2301.4     292          2301.7
Permanent Ineff=
       F       F
Bank Sta=263.2367,280.7367
XS Rating Curve= 0 ,0
Exp/Cntr(USF)=0,0
Exp/Cntr=0.5,0.3

Type RM Length L Ch R = 1 ,10301   ,96.9,96.8,96.6
BEGIN DESCRIPTION:
Structure XS 2; 18.2 ft between structure and xs
END DESCRIPTION:
XS GIS Cut Line= 5
2215068.27248342440123.919759706 2215051.9630271440115.207592726
2214869.81674258440235.353444238 2214767.6168347440241.298085583
2214492.82542335440096.663381561
#Sta/Elev= 30
       0 2300.87    18.5    2300    80.4 2301.44   137.5 2303.54   172.8 2303.51
   214.7 2301.58   246.4 2301.13   250.4 2299.72   254.4 2297.66266.22722293.728
   274.4 2292.62   282.4 2292.77   285.4 2293.74   290.4 2296.38   298.4 2297.86
   310.5 2301.74   334.5 2302.37     343 2303.18     352 2303.36   406.2 2301.17
   445.4 2301.49   454.2 2302.23   478.6 2305.44   492.1 2306.38   528.3 2306.69
   550.9 2306.04   564.4 2307.15   581.6 2307.84   617.1 2310.95   649.6 2312.85
#Mann= 5 ,-1,0
       0     .06       0266.2272    .045       0   285.4     .06       0
  296.69     .07       0  409.07     .05       0
#XS Ineff= 2 , 0
             260  2301.7     291          2301.4
Permanent Ineff=
       F       F
Bank Sta=266.2272,285.4
XS Rating Curve= 0 ,0
Exp/Cntr(USF)=0,0
Exp/Cntr=0.5,0.3

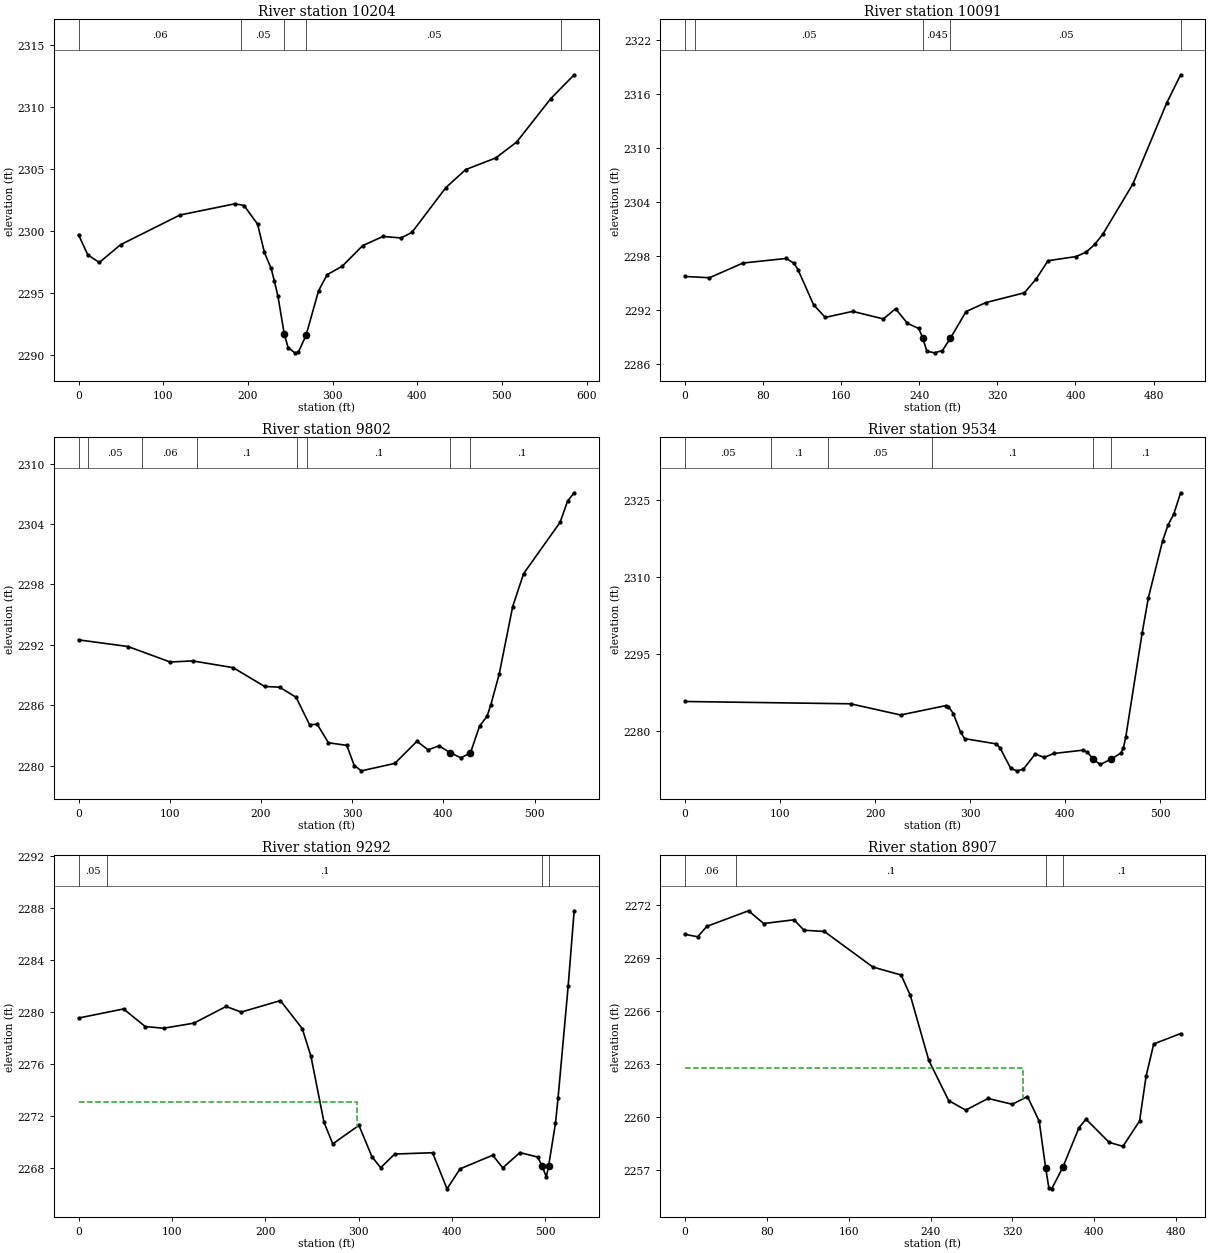
Type RM Length L Ch R = 1 ,10204   ,112.2,113,113.6
BEGIN DESCRIPTION:
Structure XS 1
END DESCRIPTION:
XS GIS Cut Line= 5
 2215082.3709595  440103.14305812215046.75375675440088.302556953
2214967.35707562440138.0182357952214740.29740807440145.438486369
2214529.56229178 440063.81573006
#Sta/Elev= 30
       0 2299.71      11 2298.08    24.6 2297.47    49.8 2298.91   119.7  2301.3
   184.9 2302.21   195.5 2302.07   211.5 2300.56   219.5 2298.29   227.5 2296.99
   231.4 2295.94   235.5 2294.76     243 2291.69   247.5  2290.6   255.5 2290.17
   259.5  2290.2   268.8  2291.6   283.5 2295.18   293.6 2296.48   311.5 2297.17
   335.6 2298.83   359.6 2299.57     381 2299.45   393.8  2299.9   433.9 2303.52
   457.2 2304.97   492.7 2305.91   517.4 2307.19   557.6 2310.69   585.4 2312.63
#Mann= 5 ,-1,0
       0     .06       0  192.26     .05       0     243    .045       0
   268.8     .05       0  569.44     .06       0
Bank Sta=243,268.8
XS Rating Curve= 0 ,0
Exp/Cntr(USF)=0,0
Exp/Cntr=0.3,0.1

Type RM Length L Ch R = 1 ,10091   ,287.1,289.1,291.3
XS GIS Cut Line= 4
2215091.27526019440076.4301560352215013.98573608440030.627369935
2214735.56302622440028.2376354272214606.98187459439974.375911121
#Sta/Elev= 30
       0 2295.75    25.1 2295.61    59.4 2297.24   103.7 2297.75   111.7 2297.21
   115.7 2296.52   131.7 2292.62   143.7 2291.21   171.7 2291.88   203.2 2291.04
   215.7 2292.17   227.9 2290.55   239.5 2289.98243.57312288.919   247.7 2287.47
   255.6 2287.28   263.7 2287.53 271.7732288.885   287.9 2291.86   308.1 2292.85
   347.7 2293.94   359.7 2295.47   371.9  2297.5   400.7 2297.96     411 2298.46
   419.7  2299.3     428 2300.44   458.8 2306.01   493.4 2314.98   507.7 2318.12
#Mann= 5 ,-1,0
       0     .06       0      10     .05       0243.5731    .045       0
 271.773     .05       0  507.68     .06       0
Bank Sta=243.5731,271.773
XS Rating Curve= 0 ,0
Exp/Cntr(USF)=0,0
Exp/Cntr=0.3,0.1

Type RM Length L Ch R = 1 ,9802    ,256.8,268.3,280.6
XS GIS Cut Line= 4
2215146.18511444439974.7727231782214995.08163002439764.655914128
2214802.45828389439735.6154635212214712.82568114439739.139405683
#Sta/Elev= 30
       0  2292.5    54.2 2291.84   100.5  2290.3   125.1 2290.41   169.5 2289.74
     204 2287.87   220.4  2287.8   238.5  2286.8   253.2 2284.08   261.7 2284.11
   273.9 2282.28   294.1 2282.02   302.2 2280.02   310.1 2279.49   346.7 2280.23
     371 2282.43   383.1 2281.58   395.2 2281.97407.41192281.289   419.1 2280.78
429.61192281.272   439.7 2283.95   447.8 2284.91   451.9 2286.03   461.2 2289.13
   475.9 2295.81   487.9 2299.08   527.9 2304.18     536 2306.27   543.3 2307.11
#Mann= 8 ,-1,0
       0     .06       0      10     .05       0      70     .06       0
     130      .1       0     240     .05       0     250      .1       0
407.4119    .045       0429.6119      .1       0
Bank Sta=407.4119,429.6119
XS Rating Curve= 0 ,0
Exp/Cntr(USF)=0,0
Exp/Cntr=0.3,0.1

Type RM Length L Ch R = 1 ,9534    ,240.5,242,238.5
XS GIS Cut Line= 2
2215260.45697327 439893.149966872214943.56815514439479.344154293
#Sta/Elev= 30
       0 2285.71   174.2 2285.26   226.7 2283.08   274.1  2284.9   277.1 2284.73
   282.1 2283.37   289.9  2279.7   294.1 2278.47   327.4 2277.45   331.2  2276.7
   342.5 2272.67   349.2  2272.2   355.7  2272.5   368.2 2275.46   377.8 2274.83
   387.9 2275.58   418.1 2276.22   423.2 2275.83429.10472274.503   436.7 2273.44
448.38462274.499   458.4 2275.66     461 2276.64   463.5 2278.77   480.7 2299.02
   487.3 2305.95   502.3 2317.04     508  2320.1   513.9 2322.18   521.2 2326.37
#Mann= 6 ,-1,0
       0     .05       0      90      .1       0     150     .05       0
     260      .1       0429.1047    .045       0448.3846      .1       0
Bank Sta=429.1047,448.3846
XS Rating Curve= 0 ,0
Exp/Cntr(USF)=0,0
Exp/Cntr=0.3,0.1

Type RM Length L Ch R = 1 ,9292    ,383.8,384.6,379
XS GIS Cut Line= 2
2215399.95768405439794.460634243 2215125.8679334 439339.64794782
#Sta/Elev= 30
       0 2279.53    48.2 2280.23    71.5 2278.88    91.1 2278.75   123.6 2279.14
   158.1 2280.42   174.3 2279.99   216.3 2280.87   239.7 2278.72     249  2276.6
     263 2271.53   272.4 2269.88   300.4  2271.3   314.4 2268.89   323.7 2268.05
   338.8  2269.1   379.3  2269.2   394.8 2266.43   408.7 2267.96   443.7 2269.01
   454.5 2268.04   472.9 2269.21   491.9 2268.87496.82762268.152   501.2 2267.34
  503.57 2268.16     511 2271.47   513.7 2273.37   524.6 2282.01     531 2287.76
#Mann= 4 ,-1,0
       0     .05       0      30      .1       0496.8276    .045       0
  503.57      .1       0
#XS Ineff= 2 , 0
          298.48 2273.08
Permanent Ineff=
       F       F
Bank Sta=496.8276,503.57
XS Rating Curve= 0 ,0
Exp/Cntr(USF)=0,0
Exp/Cntr=0.3,0.1

Type RM Length L Ch R = 1 ,8907    ,194.5,199,196.9
XS GIS Cut Line= 2
2215621.08115114439660.1540988632215395.96005828439231.239440539
#Sta/Elev= 30
       0 2270.35    12.4 2270.21    21.4  2270.8    62.1 2271.68    76.9 2270.96
   106.6 2271.17   116.3 2270.58   136.2 2270.51   183.6  2268.5   211.2 2268.05
   220.2  2266.9   238.3 2263.22   257.7 2260.95   274.4 2260.41   296.2 2261.07
   319.9 2260.74   334.7 2261.18   346.2 2259.78 352.5042257.128   355.7 2255.99
   358.4 2255.96369.30412257.181     385 2259.41   391.9  2259.9   414.5 2258.59
     428 2258.36   444.3  2259.8   450.6 2262.32   458.1 2264.15   484.4 2264.74
#Mann= 4 ,-1,0
       0     .06       0      50      .1       0 352.504    .045       0
369.3041      .1       0
#XS Ineff= 2 , 0
           330.7 2262.78
Permanent Ineff=
       F       F
Bank Sta=352.504,369.3041
XS Rating Curve= 0 ,0
Exp/Cntr(USF)=0,0
Exp/Cntr=0.3,0.1