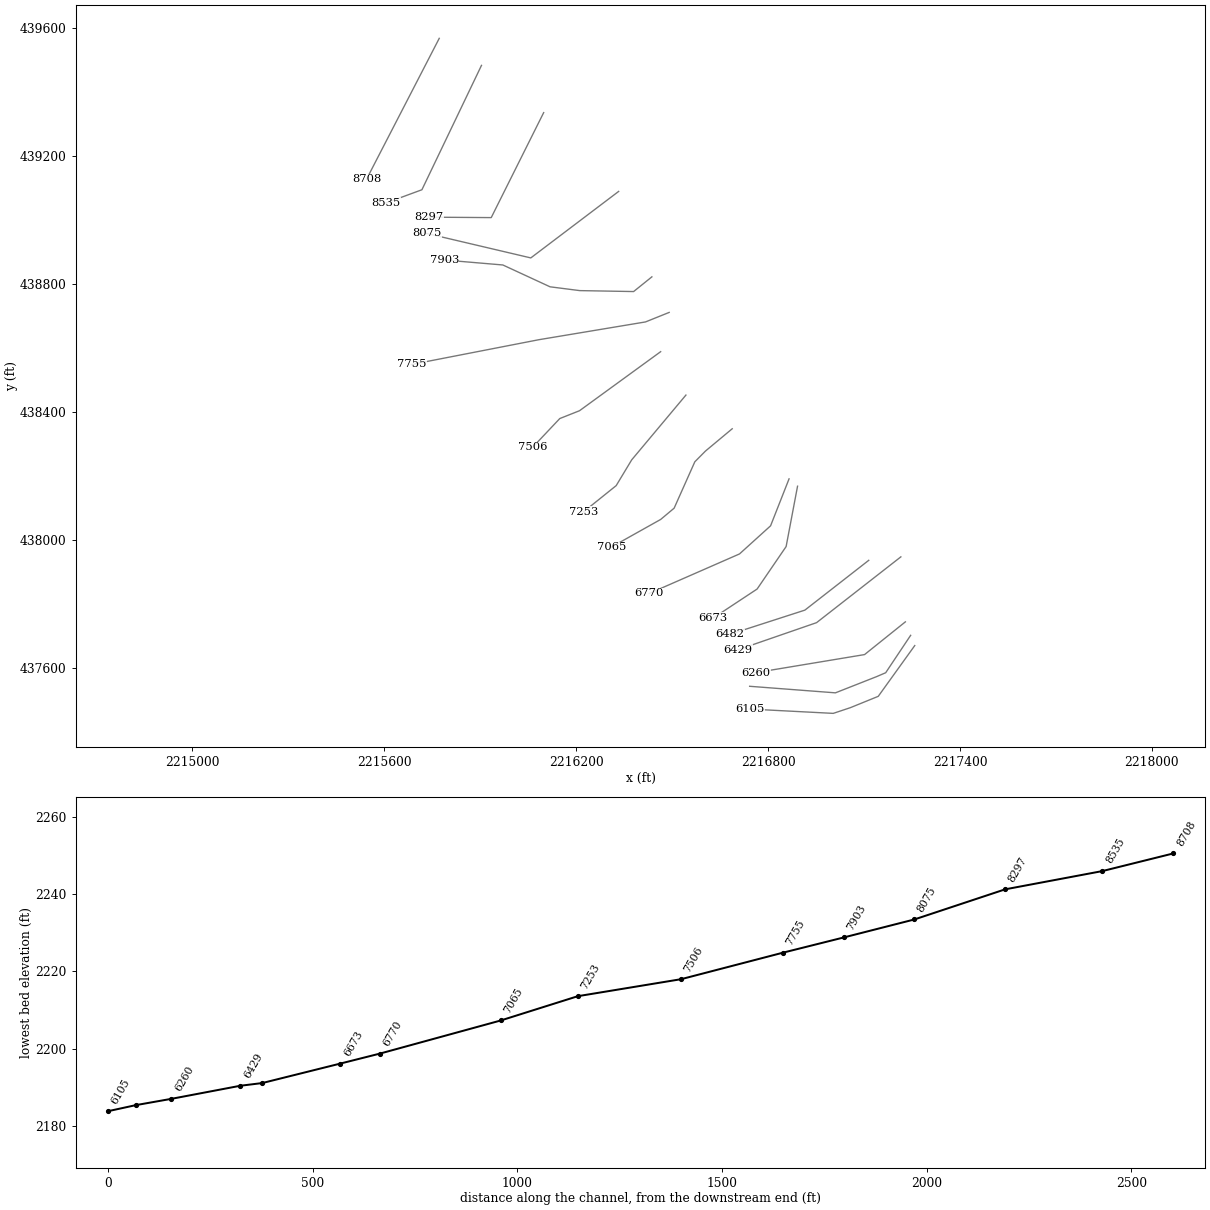
HEC-RAS study SWAGOCK.prj: SWAGOCK

--- SWAGOCK.g01 (geometry) --- (continued)

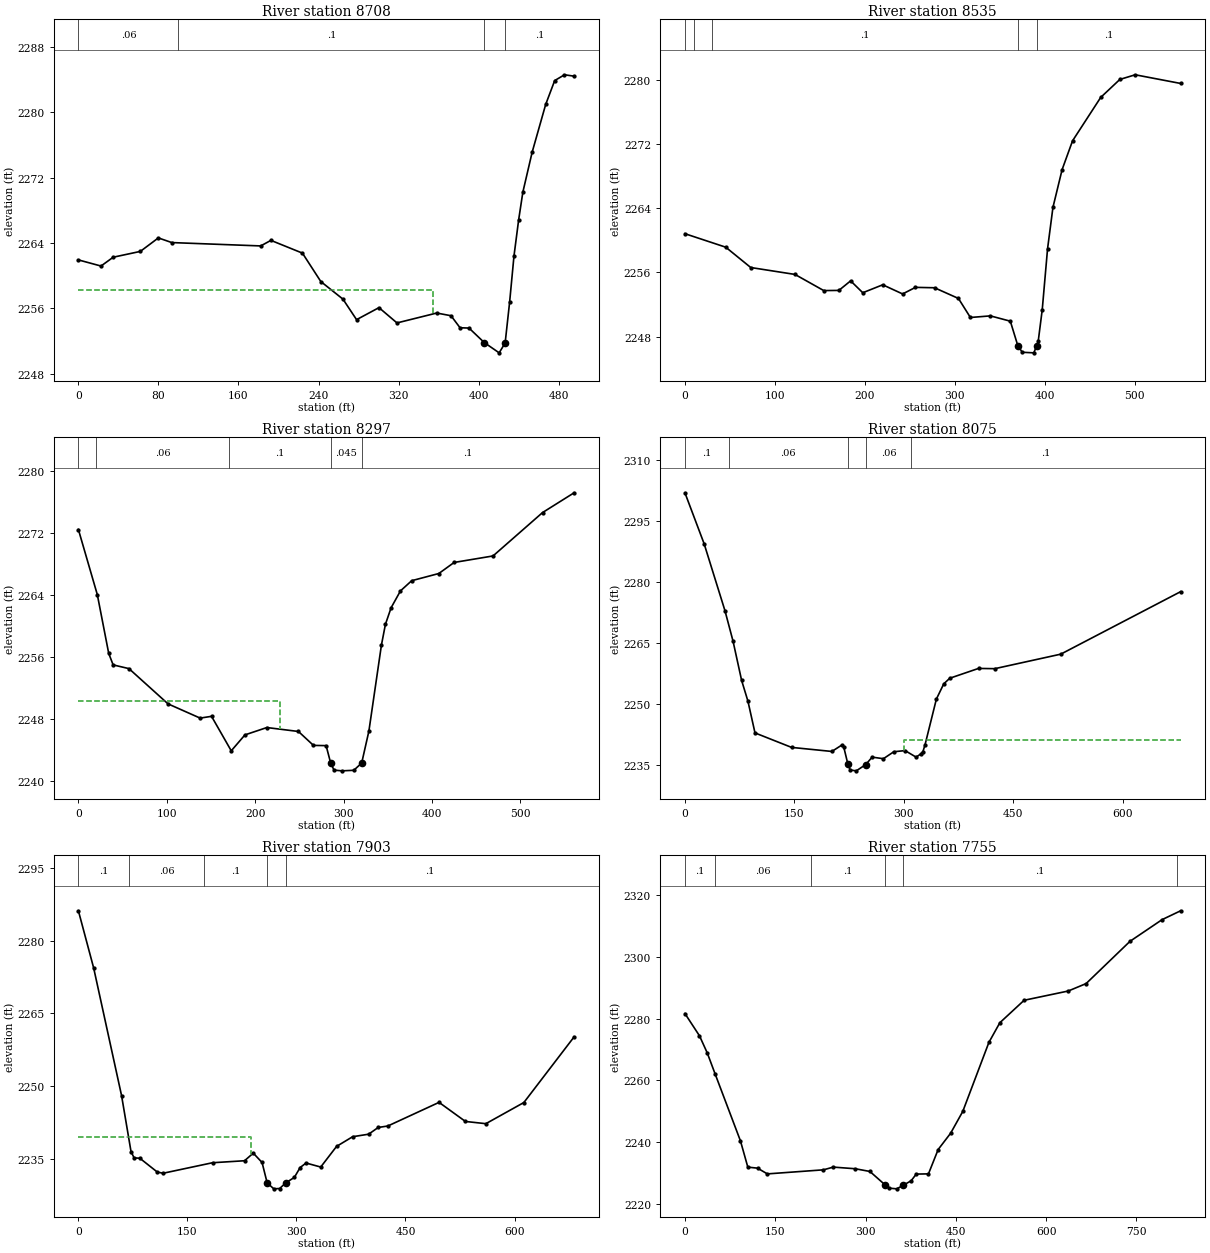
Type RM Length L Ch R = 1 ,8708    ,172.1,173.7,173.7
XS GIS Cut Line= 2
2215771.71223778439568.1429917512215544.52819094439127.925326321
#Sta/Elev= 30
       0 2261.93    22.6 2261.18    34.8 2262.26    61.9 2262.97    79.9 2264.62
    93.4 2264.05   182.2 2263.64   192.4 2264.32   223.9 2262.76   242.3 2259.28
   264.4 2257.13     278 2254.62   300.4 2256.09   318.4 2254.22   358.1 2255.43
   372.4  2255.1   381.4 2253.63   390.4 2253.59405.58292251.822   420.5 2250.56
426.48282251.767     431 2256.81   435.3 2262.39     440 2266.85   444.2 2270.23
   453.5 2275.12     467 2280.95     476 2283.87   485.8 2284.58   495.4 2284.41
#Mann= 4 ,-1,0
       0     .06       0     100      .1       0405.5829    .045       0
426.4828      .1       0
#XS Ineff= 2 , 0
          354.37 2258.29
Permanent Ineff=
       F       F
Bank Sta=405.5829,426.4828
XS Rating Curve= 0 ,0
Exp/Cntr(USF)=0,0
Exp/Cntr=0.3,0.1

Type RM Length L Ch R = 1 ,8535    ,237.7,237.5,235.5
XS GIS Cut Line= 3
2215903.79269799439483.5521352142215717.54440859439094.731005163
2215604.75659988439053.177601952
#Sta/Elev= 30
       0 2260.81    45.4 2259.13    73.2  2256.6   122.4 2255.74   154.4 2253.73
   171.2 2253.75   184.3 2254.94   197.8 2253.46     220 2254.45   242.1 2253.31
   256.4 2254.13   277.6 2254.08   304.2 2252.75   317.5 2250.38   339.7 2250.58
   361.9 2249.92   370.22246.884   375.2 2246.05     388 2245.98   391.3 2246.87
   392.9  2247.4   397.4 2251.36   403.3 2258.93   409.3 2264.09   419.5 2268.79
   431.1 2272.37   462.4 2277.77   483.7 2280.01   500.8 2280.59   551.3 2279.51
#Mann= 5 ,-1,0
       0      .1       0      10     .06       0      30      .1       0
   370.2    .045       0   391.3      .1       0
Bank Sta=370.2,391.3
XS Rating Curve= 0 ,0
Exp/Cntr(USF)=0,0
Exp/Cntr=0.3,0.1

Type RM Length L Ch R = 1 ,8297    ,229.9,222,213
XS GIS Cut Line= 3
2216098.20326301439335.8891488012215934.26596325439007.634519934
2215740.43670464439008.964987708
#Sta/Elev= 30
       0 2272.46    21.4 2264.04    34.3 2256.44    39.3 2254.95    57.2 2254.47
   101.4 2249.91   137.7 2248.07   150.6  2248.3   172.9 2243.84   188.4  2245.9
   213.2 2246.85   248.9 2246.34   265.9 2244.54   280.2 2244.51285.45032242.218
   289.2 2241.34   298.1 2241.25   311.5 2241.32320.44022242.259   328.6  2246.4
   342.8 2257.54   347.3  2260.2   353.7 2262.34   364.3 2264.52     377 2265.84
   407.7 2266.77     425  2268.2     469 2269.04     525 2274.65   560.7 2277.21
#Mann= 5 ,-1,0
       0      .1       0      20     .06       0     170      .1       0
285.4503    .045       0320.4402      .1       0
#XS Ineff= 2 , 0
          227.49 2250.22
Permanent Ineff=
       F       F
Bank Sta=285.4503,320.4402
XS Rating Curve= 0 ,0
Exp/Cntr(USF)=0,0
Exp/Cntr=0.3,0.1

Type RM Length L Ch R = 1 ,8075    ,186.4,172.4,159.6
XS GIS Cut Line= 3
2216332.68318114439089.5368297622216057.98619023438881.592307921
2215732.33242585438958.166196804
#Sta/Elev= 30
       0    2302    26.3 2289.44    54.9  2272.9    65.9 2265.43    77.7 2255.72
    86.3 2250.64      96 2242.79   146.1 2239.22   201.3 2238.22   214.8 2239.78
   217.6  2239.3223.28372235.073   226.4 2233.64   234.8 2233.44  247.65 2234.98
   256.5 2236.82   271.9 2236.43   286.2 2238.15   301.6 2238.43   316.7 2236.82
   323.3 2237.63   326.1  2238.2     329  2239.9   344.5 2251.14   354.6 2254.89
   362.8 2256.27   402.2 2258.69   424.5 2258.63   514.9 2262.21   679.1 2277.62
#Mann= 5 ,-1,0
       0      .1       0      60     .06       0223.2837    .045       0
  247.65     .06       0     310      .1       0
#XS Ineff= 2 , 0
                           300.4         2241.14
Permanent Ineff=
       F       F
Bank Sta=223.2837,247.65
XS Rating Curve= 0 ,0
Exp/Cntr(USF)=0,0
Exp/Cntr=0.3,0.1

Type RM Length L Ch R = 1 ,7903    ,143,148,154.7
XS GIS Cut Line= 6
2216436.56668917438822.4078091162216379.43075975438776.402255561
2216210.99107173 438779.370355792216118.23793956438791.242756708
2215970.57495315438859.5090619842215787.29476399438875.091588188
#Sta/Elev= 30
       0 2286.18      21 2274.38    59.4 2248.03    72.4 2236.48    76.6 2235.18
    84.6 2235.09   108.6 2232.24   116.6    2232   184.6 2234.17   228.6 2234.58
   240.6 2236.15   252.7 2234.22  259.73    2230   268.9 2228.78   276.9 2228.85
   285.3 2230.01   297.1 2231.14   305.1 2233.18   313.2 2234.11   333.4 2233.28
   355.2 2237.54   377.3 2239.54   399.3 2240.06   412.5 2241.45   425.7 2241.75
   496.2 2246.63   532.5 2242.69   560.6 2242.23   612.9  2246.6     682 2260.15
#Mann= 5 ,-1,0
       0      .1       0      70     .06       0  173.36      .1       0
  259.73    .045       0   285.3      .1       0
#XS Ineff= 2 , 0
           237.8 2239.41
Permanent Ineff=
       F       F
Bank Sta=259.73,285.3
XS Rating Curve= 0 ,0
Exp/Cntr(USF)=0,0
Exp/Cntr=0.3,0.1

Type RM Length L Ch R = 1 ,7755    ,245.4,249.3,251
XS GIS Cut Line= 4
2216490.58915799438711.1751192622216416.63919064 438681.44079479
2216083.51537372438625.9102010792215684.91258666438548.371769935
#Sta/Elev= 30
       0 2281.64    24.2 2274.42    37.1 2268.88      50 2262.16    92.3 2240.36
   104.5 2231.88   120.7 2231.55   136.9 2229.69   230.2 2231.01   246.4 2231.89
   282.9 2231.36   307.3 2230.48     333 2226.05   339.7 2225.07   351.9 2224.85
   362.2 2225.96   375.8 2227.46   384.3 2229.63   404.6  2229.7   420.7 2237.59
   441.4 2242.86   461.6 2249.93     505 2272.29   523.2 2278.66   563.5 2285.93
   636.8 2288.93   666.5 2291.34   739.4 2305.03   792.7 2312.05   823.5 2314.92
#Mann= 6 ,-1,0
       0      .1       0      50     .06       0   209.7      .1       0
     333    .045       0   362.2      .1       0  817.42     .05       0
Bank Sta=333,362.2
XS Rating Curve= 0 ,0
Exp/Cntr(USF)=0,0
Exp/Cntr=0.3,0.1

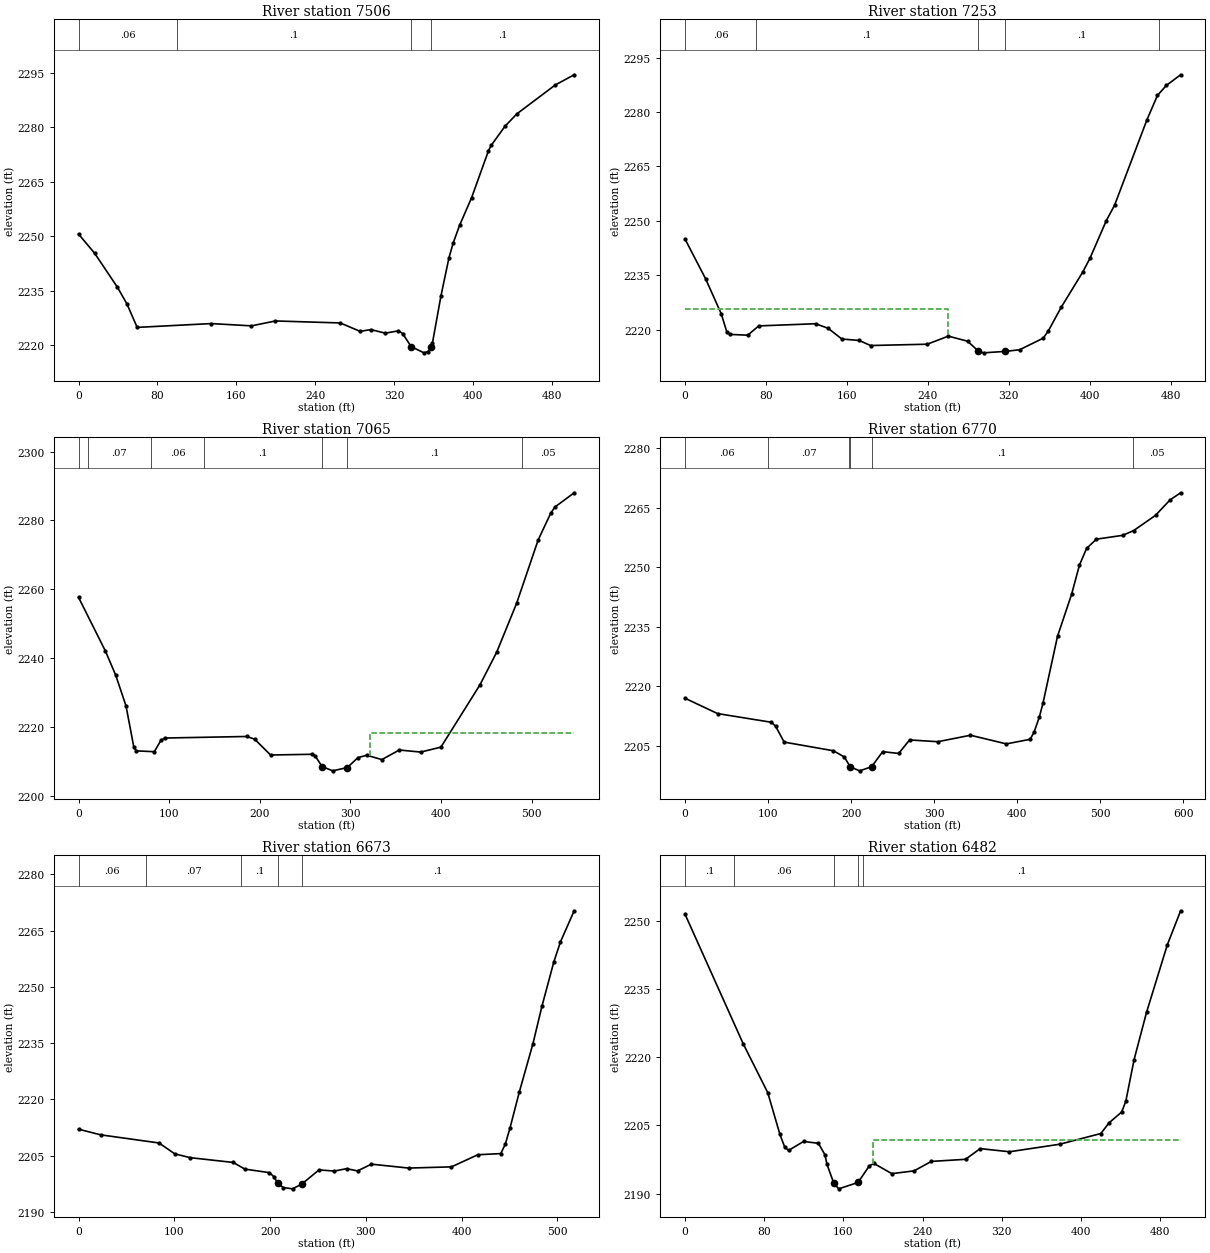
Type RM Length L Ch R = 1 ,7506    ,240.2,252.1,261.4
XS GIS Cut Line= 4
2216463.98108171438588.4281131232216210.30940263438403.820833333
2216148.59155368438379.329623435 2216064.2692381438290.103961266
#Sta/Elev= 30
       0 2250.65    16.5 2245.31    39.5 2236.01    49.2 2231.39    59.5 2224.97
   134.7 2226.02   175.5 2225.39   199.8 2226.74   265.6 2226.19   285.7 2223.88
   296.6 2224.36   311.4 2223.38   324.6 2224.03   328.9 2223.27   337.5 2219.68
   350.5 2217.97   354.8 2218.33   357.5 2219.65   359.1 2220.65   367.7 2233.57
   375.9 2244.15   380.1 2248.13   386.6 2253.01   398.9 2260.69   415.9 2273.51
   418.7 2275.02   432.6 2280.25   444.8 2283.71   483.8 2291.66   502.9 2294.45
#Mann= 4 ,-1,0
       0     .06       0     100      .1       0   337.5    .045       0
   357.5      .1       0
Bank Sta=337.5,357.5
XS Rating Curve= 0 ,0
Exp/Cntr(USF)=0,0
Exp/Cntr=0.3,0.1

Type RM Length L Ch R = 1 ,7253    ,186.2,188.5,190.8
XS GIS Cut Line= 4
2216542.99690048438452.741918509 2216373.5220417438250.288168295
2216324.96978486438169.6731003362216222.36878928438087.225871741
#Sta/Elev= 30
       0 2244.98    20.3 2234.05    35.8 2224.38    41.4 2219.28    44.3 2218.66
      62 2218.44    72.9    2221     129  2221.6   141.5 2220.34     155 2217.38
   172.1 2216.99   183.4 2215.59   239.4 2215.95   260.3 2218.18   279.3 2216.77
   289.9 2214.05     295 2213.57   316.72213.975   330.7 2214.42     354 2217.62
   359.2 2219.68   371.7 2226.11   393.2 2235.92   400.2 2239.66   416.4 2250.07
   424.5 2254.29   456.6 2277.93   466.9 2284.59   475.7 2287.36   489.8 2290.29
#Mann= 5 ,-1,0
       0     .06       0      70      .1       0   289.9    .045       0
   316.7      .1       0  468.13     .05       0
#XS Ineff= 2 , 0
          260.28 2225.66
Permanent Ineff=
       F       F
Bank Sta=289.9,316.7
XS Rating Curve= 0 ,0
Exp/Cntr(USF)=0,0
Exp/Cntr=0.3,0.1

Type RM Length L Ch R = 1 ,7065    ,298.9,295.2,286.4
XS GIS Cut Line= 6
2216687.73759068438347.3926819722216604.06430698438277.666933041
2216570.82001232438244.1381447982216506.16321819438099.150182203
2216464.03833717438063.8828399492216309.51950099437977.310508953
#Sta/Elev= 30
       0 2257.69    29.7 2242.06      41 2235.09    52.4 2226.15    60.9 2214.34
    63.7 2213.07    83.6 2212.83    90.9 2216.09      95  2216.8   185.7 2217.25
   194.4 2216.46   211.9 2211.87   257.3 2212.08   260.8 2211.72268.84942208.501
   280.5 2207.27296.64942208.239   308.3  2211.1     318  2211.8   334.7 2210.54
     354 2213.32   377.6 2212.72   399.9 2214.16     443 2232.28   461.4 2241.73
   483.4 2255.94   507.2 2274.36     521 2282.09   525.6  2283.9   546.9 2288.05
#Mann= 7 ,-1,0
       0      .1       0      10     .07       0      80     .06       0
  138.92      .1       0268.8494    .045       0296.6494      .1       0
  489.82     .05       0
#XS Ineff= 2 , 0
                          321.46         2218.12
Permanent Ineff=
       F       F
Bank Sta=268.8494,296.6494
XS Rating Curve= 0 ,0
Exp/Cntr(USF)=0,0
Exp/Cntr=0.3,0.1

Type RM Length L Ch R = 1 ,6770    ,93,96.5,99.6
XS GIS Cut Line= 4
2216865.45717231438190.742947643 2216807.6866556438043.964010195
2216710.50326194437956.0361778372216428.45796835437832.495933963
#Sta/Elev= 30
       0 2216.99    39.2 2213.12     104 2210.93   109.1 2209.94   119.4 2205.93
   178.7 2203.75   191.7  2202.2199.0496 2199.68   210.3 2198.69224.64962199.727
     238 2203.52   257.3 2203.07   270.4 2206.48   304.4 2206.03   343.7 2207.66
   386.9 2205.48   415.6 2206.64   420.3 2208.46   426.7 2212.31   431.1 2215.84
   448.5 2232.62   465.4 2243.15   474.9 2250.54   483.5 2254.74   495.3 2257.07
   527.1 2258.04   540.3 2259.25   566.5 2263.08   583.9 2266.95   596.7 2268.76
#Mann= 6 ,-1,0
       0     .06       0     100     .07       0  197.74      .1       0
199.0496    .045       0224.6496      .1       0   538.8     .05       0
Bank Sta=199.0496,224.6496
XS Rating Curve= 0 ,0
Exp/Cntr(USF)=0,0
Exp/Cntr=0.3,0.1

Type RM Length L Ch R = 1 ,6673    ,196.4,190.9,186.1
XS GIS Cut Line= 4
2216892.02350153  438167.84093972216856.29636913437979.128394251
2216765.60441768437846.2967481832216628.19237002437755.604796729
#Sta/Elev= 30
       0 2212.02    23.1 2210.51    84.1 2208.34   100.4 2205.45   116.7 2204.42
   161.5 2203.15   173.7 2201.37   199.3 2200.43   204.1 2199.32   207.9 2197.59
   213.8 2196.46   223.5 2196.11   233.2  2197.4   251.1 2201.16   267.1 2200.85
   279.9 2201.49   291.3 2200.89   305.8 2202.69   344.6 2201.65   389.4 2201.97
   416.9  2205.2   440.9 2205.51   445.7 2208.09   450.5 2212.32   460.1 2221.81
   474.4 2234.76     484 2244.94   496.2 2256.56   503.2 2261.98   517.5 2270.26
#Mann= 5 ,-1,0
       0     .06       0      70     .07       0     170      .1       0
   207.9    .045       0   233.2      .1       0
Bank Sta=207.9,233.2
XS Rating Curve= 0 ,0
Exp/Cntr(USF)=0,0
Exp/Cntr=0.3,0.1

Type RM Length L Ch R = 1 ,6482    ,53.7,53.5,54
XS GIS Cut Line= 3
2217114.63101873437936.0726193192216914.92550947437780.338965307
2216679.49286782437704.304298937
#Sta/Elev= 30
       0 2251.45    58.9 2222.91    83.6 2212.21    95.8 2203.11   100.7 2200.25
   104.6  2199.5   119.8 2201.47   134.8 2201.07   141.3 2198.58   143.5 2196.42
   150.2 2192.38   155.3 2191.06   174.8 2192.46   186.2  2196.1   190.8 2196.64
     209  2194.4   231.4 2195.01   248.9 2197.09   283.4 2197.55   298.2  2199.9
   327.8 2199.21   378.7 2200.87   420.1 2203.22   428.5 2205.59   441.1 2207.94
   445.3 2210.29   453.7 2219.48   466.3 2229.89   487.3 2244.73   500.7 2252.18
#Mann= 5 ,-1,0
       0      .1       0      50     .06       0   150.2    .045       0
   174.8     .06       0     180      .1       0
#XS Ineff= 2 , 0
                          190.31         2201.69
Permanent Ineff=
       F       F
Bank Sta=150.2,174.8
XS Rating Curve= 0 ,0
Exp/Cntr(USF)=0,0
Exp/Cntr=0.3,0.1

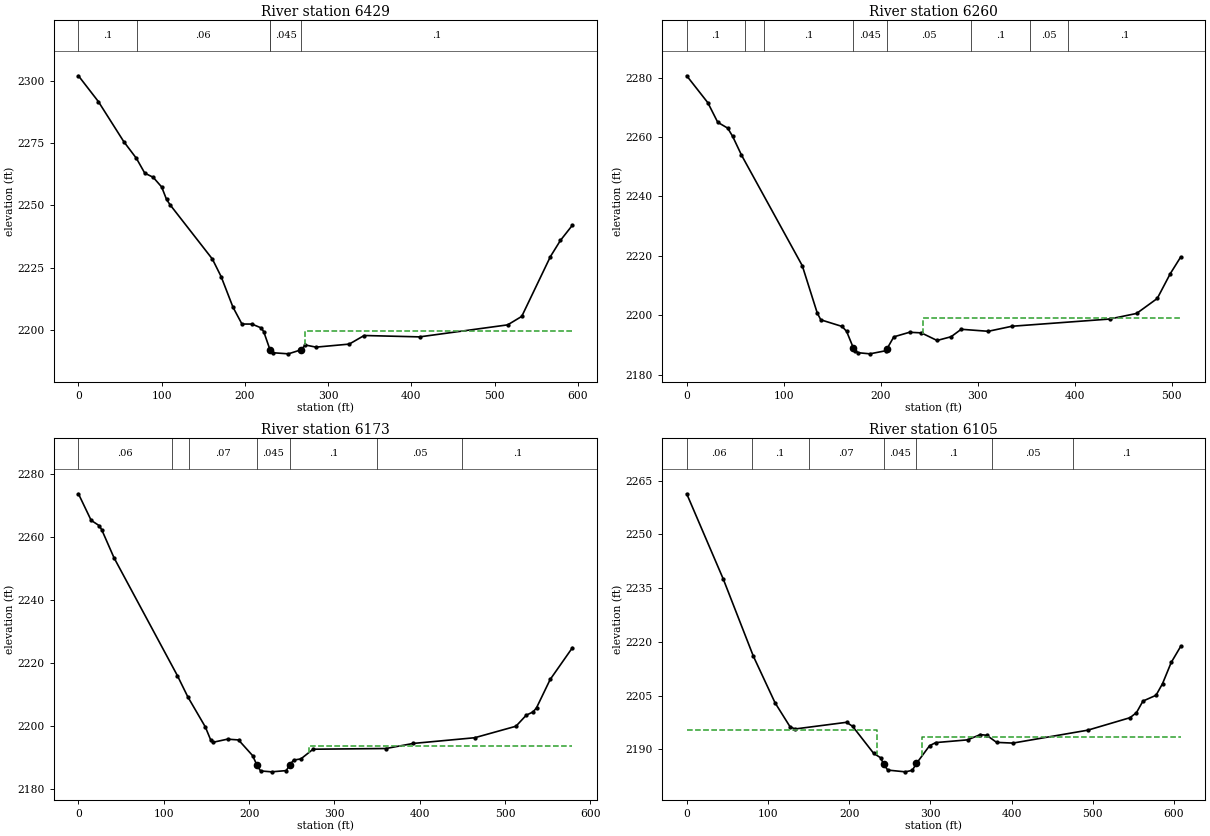
Type RM Length L Ch R = 1 ,6429    ,179.3,168.5,156.3
XS GIS Cut Line= 3
2217214.99849388437946.8971451442216951.47307538437741.170982001
2216706.61178731437656.579281006
#Sta/Elev= 30
       0 2301.98    23.9 2291.65    54.5 2275.53    69.6 2268.86    79.7 2262.89
    89.8 2261.23     100 2257.34   105.8 2252.37   110.1 2250.19   160.9 2228.41
   171.4 2221.38   185.6 2209.12   196.4 2202.33   208.4 2202.31   219.8 2200.73
   222.7 2199.16   230.3 2191.81   234.1 2190.79   252.2 2190.36   267.5 2191.98
   272.5 2193.91   285.4 2193.05   325.3 2194.27   343.2 2197.72   409.8 2197.17
   515.6 2201.99   532.5 2205.39     567 2229.43     579  2235.9   593.4 2242.01
#Mann= 5 ,-1,0
       0      .1       0      70     .06       0     230      .1       0
   230.3    .045       0   267.5      .1       0
#XS Ineff= 2 , 0
                          272.67         2199.68
Permanent Ineff=
       F       F
Bank Sta=230.3,267.5
XS Rating Curve= 0 ,0
Exp/Cntr(USF)=0,0
Exp/Cntr=0.3,0.1

Type RM Length L Ch R = 1 ,6260    ,81,87.3,91.5
BEGIN DESCRIPTION:
Structure XS 4
END DESCRIPTION:
XS GIS Cut Line= 3
2217229.14105844437743.695752599 2217101.5507269437641.347093609
2216760.25190393437584.656780641
#Sta/Elev= 30
       0 2280.58    21.8 2271.51      32 2264.92    42.3 2262.95    47.4 2260.17
    56.5 2253.88   119.2 2216.64   134.6 2200.75   138.3 2198.42   160.2  2196.2
   164.9 2194.54171.84512188.989   173.1 2187.99   177.1 2187.34     189 2186.97
   205.5 2188.03206.64512188.716   213.6 2192.69   229.8 2194.23     242 2194.03
   258.2 2191.47   272.7 2192.73   283.1 2195.24     311 2194.56   335.5 2196.26
   436.1 2198.68     464 2200.57   485.3 2205.61   498.7 2213.94   509.5 2219.58
#Mann= 8 ,-1,0
       0      .1       0      60     .06       0      80      .1       0
171.8451    .045       0206.6451     .05       0  293.57      .1       0
  353.57     .05       0  393.57      .1       0
#XS Ineff= 2 , 0
                          243.72         2199.13
Permanent Ineff=
       F       F
Bank Sta=171.8451,206.6451
XS Rating Curve= 0 ,0
Exp/Cntr(USF)=0,0
Exp/Cntr=0.5,0.3

Type RM Length L Ch R = 1 ,6173    ,65.4,67.7,66.8
BEGIN DESCRIPTION:
Structure XS 3; 25.6 ft between structure and xs
END DESCRIPTION:
XS GIS Cut Line= 5
2217245.63050416437701.5560579842217167.57798069437584.587745723
2217138.88506963 437572.29078384 2217010.4501344437521.736607209
2216742.22126351437542.223656786
#Sta/Elev= 30
       0 2273.81    14.9 2265.36    24.4 2263.66    27.3 2262.37    41.7 2253.45
   115.9 2215.98   128.2 2209.18   148.7 2199.62   154.9 2195.54     158 2194.75
   174.7 2195.73   187.6 2195.48   204.1  2190.5   209.1 2187.52   213.4 2185.62
   226.3 2185.33   243.5 2185.72   247.8  2187.6   252.1 2189.06   260.7 2189.45
     275 2192.53   360.3 2192.75   392.4 2194.37   464.3 2196.18   512.7 2199.84
   524.8 2203.36   532.8  2204.4   536.8  2205.7   552.8 2214.72   578.9 2224.84
#Mann= 7 ,-1,0
       0     .06       0     110      .1       0     130     .07       0
   209.1    .045       0   247.8      .1       0  349.86     .05       0
  449.86      .1       0
#XS Ineff= 2 , 0
             185  2195.4     270          2193.4
Permanent Ineff=
       F       F
Bank Sta=209.1,247.8
XS Rating Curve= 0 ,0
Exp/Cntr(USF)=0,0
Exp/Cntr=0.5,0.3

Type RM Length L Ch R = 1 ,6105    ,58.4,48.4,42.5
BEGIN DESCRIPTION:
Structure XS 2; 23.3 ft between structure and xs
END DESCRIPTION:
XS GIS Cut Line= 5
2217258.45562861437669.4932468642217144.35038602437510.805974424
2217056.90532374437475.2814178732217003.61848891437457.519139597
2216741.75300273437471.079789503
#Sta/Elev= 30
       0 2261.34      45 2237.55    82.1    2216   108.8 2203.01   127.2 2196.35
   133.4 2195.72   196.8 2197.58   204.3 2196.45   230.2 2188.91   238.8 2187.68
   242.3 2185.94   247.5 2184.25     269 2183.76   277.7 2184.17   282.8 2186.09
     299 2191.05   306.6 2191.92   345.8 2192.68   361.5 2194.16   369.5 2193.95
   381.5 2191.98   401.5 2191.78   493.7 2195.38   545.7 2198.86   553.7 2200.27
   561.7  2203.5   577.8 2205.12   585.8 2208.36   596.5 2214.28   608.2 2218.77
#Mann= 7 ,-1,0
       0     .06       0      80      .1       0     150     .07       0
   242.3    .045       0   282.8      .1       0  376.01     .05       0
  476.01      .1       0
#XS Ineff= 2 , 0
             234  2195.4     290          2193.4
Permanent Ineff=
       F       F
Bank Sta=242.3,282.8
XS Rating Curve= 0 ,0
Exp/Cntr(USF)=0,0
Exp/Cntr=0.5,0.3