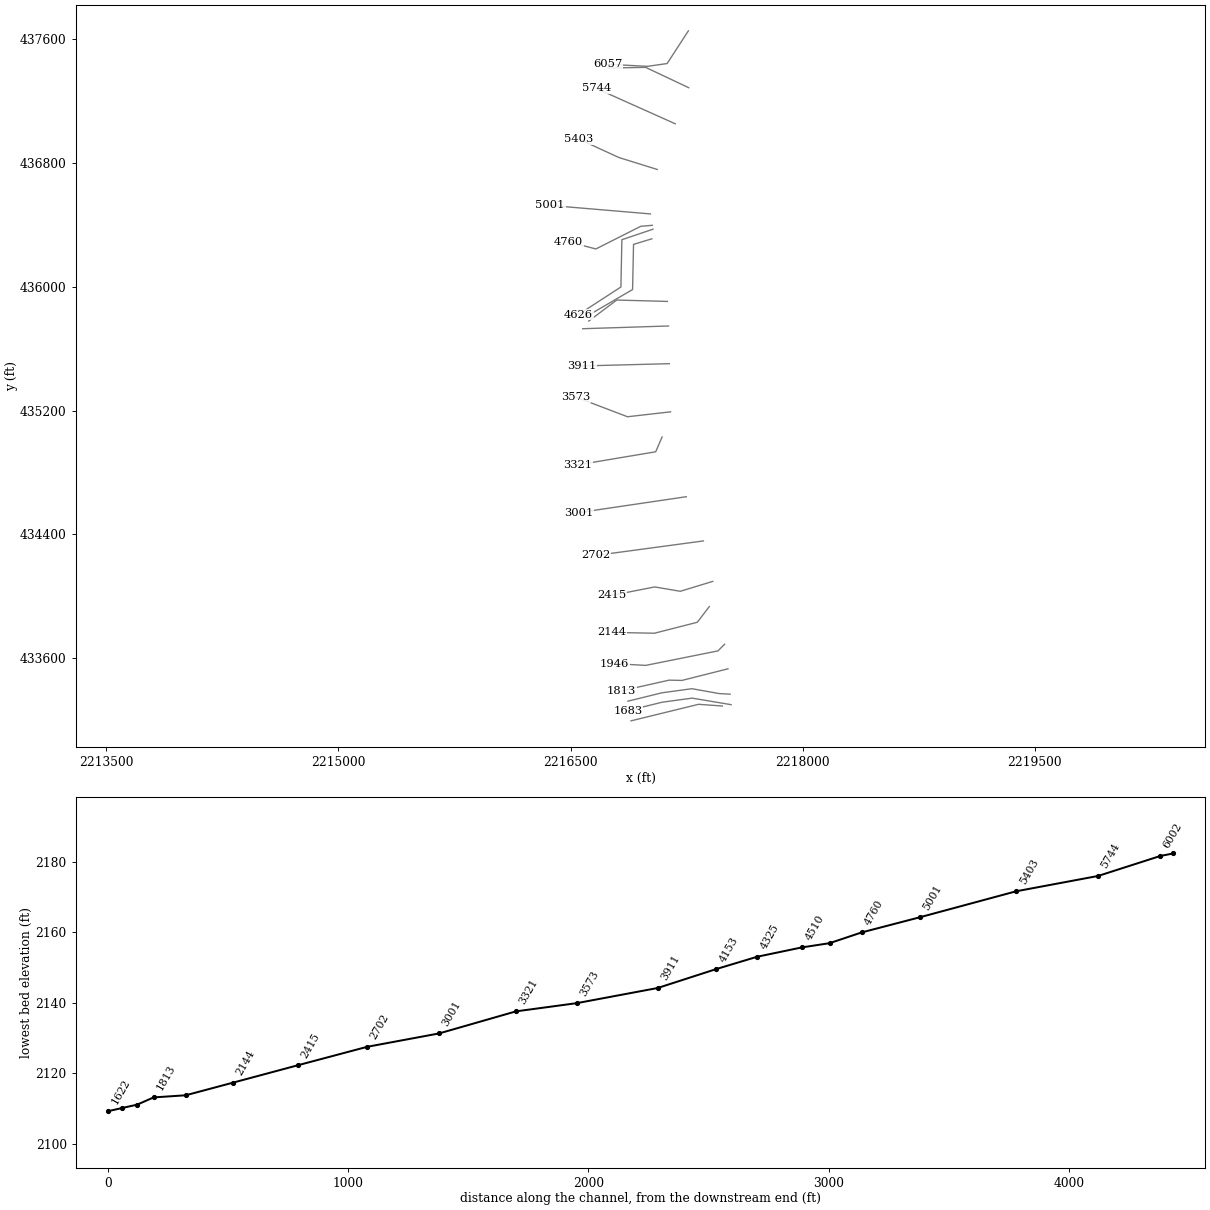
HEC-RAS study SWAGOCK.prj: SWAGOCK

--- SWAGOCK.g01 (geometry) --- (continued)

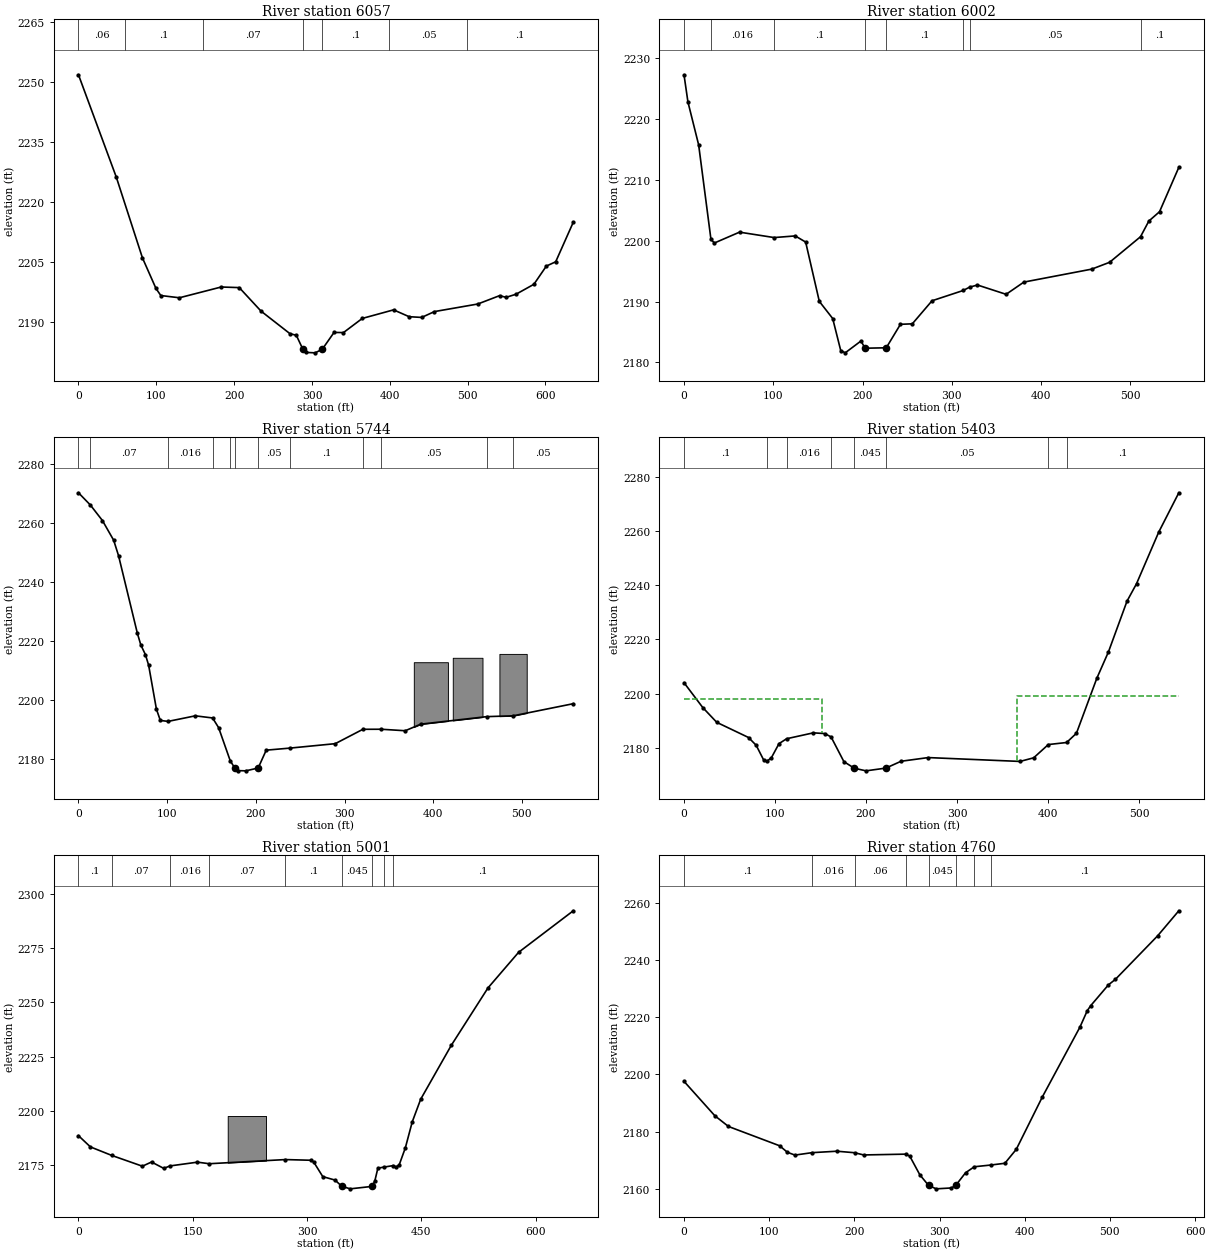
Type RM Length L Ch R = 1 ,6057    ,67.9,54.8,47.9
BEGIN DESCRIPTION:
Structure XS 1
END DESCRIPTION:
XS GIS Cut Line= 4
2217261.20386956437653.919881463 2217123.9963286437442.816928237
2216997.42386836437424.7106885872216741.59569693437438.070016035
#Sta/Elev= 30
       0 2251.78    48.6 2226.21    82.2 2206.03    99.6 2198.38   105.8 2196.62
   129.7 2196.06   183.4 2198.75   206.6  2198.6   234.6 2192.72   271.8 2187.08
   279.9 2186.69288.40212183.179     292 2182.41   304.1  2182.3313.2021 2183.18
   328.4  2187.4   340.5 2187.36   364.7  2190.9   404.9 2193.04   424.9 2191.33
     441 2191.15   457.4 2192.61   513.1  2194.5   541.1 2196.59   549.5 2196.17
   562.2 2196.94   585.2 2199.43   601.2 2203.98   613.2 2205.05   635.8 2214.94
#Mann= 7 ,-1,0
       0     .06       0      60      .1       0     160     .07       0
288.4021    .045       0313.2021      .1       0  399.64     .05       0
  499.64      .1       0
Bank Sta=288.4021,313.2021
XS Rating Curve= 0 ,0
Exp/Cntr(USF)=0,0
Exp/Cntr=0.3,0.1

Type RM Length L Ch R = 1 ,6002    ,257.9,258.8,257.3
BEGIN DESCRIPTION:
Upstream of this XS:  Zone A
Downstrema of this XS:  Zone AE
END DESCRIPTION:
XS GIS Cut Line= 3
2217263.45448664437286.6169125942216984.94039711437418.210764739
2216738.66878455437413.716757211
#Sta/Elev= 30
       0 2227.28     4.4 2222.81    16.4 2215.76    30.2 2200.21    34.1 2199.63
    62.2 2201.41     101 2200.52   124.6 2200.79   136.3 2199.78   151.6 2190.03
   166.6 2187.21   175.6 2181.95   180.6 2181.57   198.3 2183.52202.80762182.329
226.60752182.401   242.5 2186.26   255.8 2186.34   277.9 2190.13   312.8 2191.82
     320 2192.37   328.8 2192.72   360.9 2191.19   380.8  2193.2   456.8 2195.33
   476.8 2196.45   511.5 2200.66   520.8 2203.23   532.8 2204.77   554.4 2212.06
#Mann= 8 ,-1,0
       0     .07       0    30.2    .016       0     101      .1       0
202.8076    .045       0226.6075      .1       0   312.8    .016       0
     320     .05       0   511.5      .1       0
Bank Sta=202.8076,226.6075
XS Rating Curve= 0 ,0
Exp/Cntr(USF)=0,0
Exp/Cntr=0.3,0.1

Type RM Length L Ch R = 1 ,5744    ,338.4,340.8,353.9
XS GIS Cut Line= 2
2217176.37030829437053.6384614222216667.17668934437281.722120371
#Sta/Elev= 30
       0 2270.29    13.4 2266.14      27 2260.87    39.7 2254.18    45.2 2248.92
    66.4 2222.61    70.3 2218.64    75.5 2215.34    79.1 2211.78    87.9 2196.83
    92.3 2193.02     101 2192.69   131.7 2194.58   151.2 2193.86     158 2190.58
   171.1 2179.34     176 2176.98   179.9 2175.98   188.7 2175.91   202.6 2176.87
   211.7 2182.93   238.9 2183.64   289.5 2185.13   320.7 2190.01   341.3 2190.03
   368.4 2189.52   385.9 2191.75   460.4 2194.31   490.2 2194.59   557.9  2198.7
#Mann= 12 ,-1,0
       0      .1       0    13.4     .07       0     101    .016       0
   151.2     .06       0   171.1      .1       0     176    .045       0
   202.6     .05       0   238.9      .1       0   320.7    .016       0
   341.3     .05       0   460.4    .016       0   490.2     .05       0
#Block Obstruct= 3 ,-1
  378.09  416.55 2212.78  422.03  455.54 2214.28  474.61   505.4  2215.6
Bank Sta=176,202.6
XS Rating Curve= 0 ,0
Exp/Cntr(USF)=0,0
Exp/Cntr=0.3,0.1

Type RM Length L Ch R = 1 ,5403    ,390,401.8,381.5
Node Name=B
XS GIS Cut Line= 3
2217059.88108271436758.4570257142216812.25560207436835.654032218
 2216553.9047725436954.406856812
#Sta/Elev= 30
       0 2204.07    20.6 2194.91      36 2189.45    70.9 2183.86    79.3 2180.99
    87.7 2175.46    91.4 2175.15    96.1 2176.46   104.4 2181.61   112.8 2183.41
   142.1 2185.58   154.7 2185.31   161.6 2184.07   175.7 2174.95   187.2 2172.52
     200 2171.57   221.8 2172.58   238.5  2175.1   268.3 2176.46   369.2 2175.04
   384.2 2176.37   400.3 2181.26   420.4 2182.02   431.2 2185.42   453.6  2205.7
   466.4 2215.45   486.8 2234.16   497.2 2240.55   521.6 2259.58   543.7  2274.1
#Mann= 8 ,-1,0
       0      .1       0    91.4     .06       0   112.8    .016       0
   161.6     .06       0   187.2    .045       0   221.8     .05       0
   400.3    .016       0   420.4      .1       0
#XS Ineff= 2 , 0
          151.77 2197.99  365.58         2199.34
Permanent Ineff=
       F       F
Bank Sta=187.2,221.8
XS Rating Curve= 0 ,0
Exp/Cntr(USF)=0,0
Exp/Cntr=0.3,0.1

Type RM Length L Ch R = 1 ,5001    ,226.6,241.4,254.1
XS GIS Cut Line= 2
2217015.77351185436471.1923334932216368.58198025436526.062874014
#Sta/Elev= 30
       0 2188.64    15.7 2183.47    43.8 2179.54    83.9  2174.6    95.9 2176.53
     112 2173.59     120 2174.72   156.2 2176.46   171.7 2175.74   271.6 2177.65
   304.7 2177.34   308.7 2176.56   320.7  2169.8   336.8 2168.22   345.6 2165.37
   356.7 2164.19  385.63 2165.32     389 2167.83     393 2173.69     401 2174.19
   413.1 2174.88   417.1  2174.2   421.1 2175.32   429.1 2183.08   438.1 2194.97
   449.2  2205.4   489.3 2230.15   537.5 2256.58   577.7 2272.96   649.5 2292.07
#Mann= 9 ,-1,0
       0      .1       0    43.8     .07       0     120    .016       0
   171.7     .07       0   271.6      .1       0   345.6    .045       0
  385.63      .1       0     401    .016       0   413.1      .1       0
#Block Obstruct= 1 ,-1
  195.91  246.21 2197.69
Bank Sta=345.6,385.63
XS Rating Curve= 0 ,0
Exp/Cntr(USF)=0,0
Exp/Cntr=0.3,0.1

Type RM Length L Ch R = 1 ,4760    ,99.3,133.7,162.2
BEGIN DESCRIPTION:
Structure XS 4
END DESCRIPTION:
XS GIS Cut Line= 4
2217028.21410876436397.6797154052216953.22977684436390.994770908
2216663.67690446436244.8736619392216488.12268157436290.258713129
#Sta/Elev= 30
       0 2197.59    36.2 2185.53    52.2 2181.77   112.3    2175   121.3 2172.74
   130.2 2171.74   150.3 2172.59   179.5  2173.1   200.2 2172.57   210.9 2171.79
   260.2 2172.07     265 2171.39   276.9 2164.81287.05892161.136     296 2159.91
   313.9 2160.22319.0589 2161.14   330.5 2165.54   340.8 2167.65   360.3 2168.26
   376.7 2168.87   390.1 2173.77   420.8 2192.19   464.8 2216.59   473.5 2222.41
   477.6 2224.17   498.3 2231.42   506.5 2233.36   556.1 2248.62   580.9 2257.38
#Mann= 8 ,-1,0
       0      .1       0   150.3    .016       0   200.2     .06       0
   260.2      .1       0287.0589    .045       0319.0589      .1       0
   340.8    .016       0   360.3      .1       0
Bank Sta=287.0589,319.0589
XS Rating Curve= 0 ,0
Exp/Cntr(USF)=0,0
Exp/Cntr=0.5,0.3

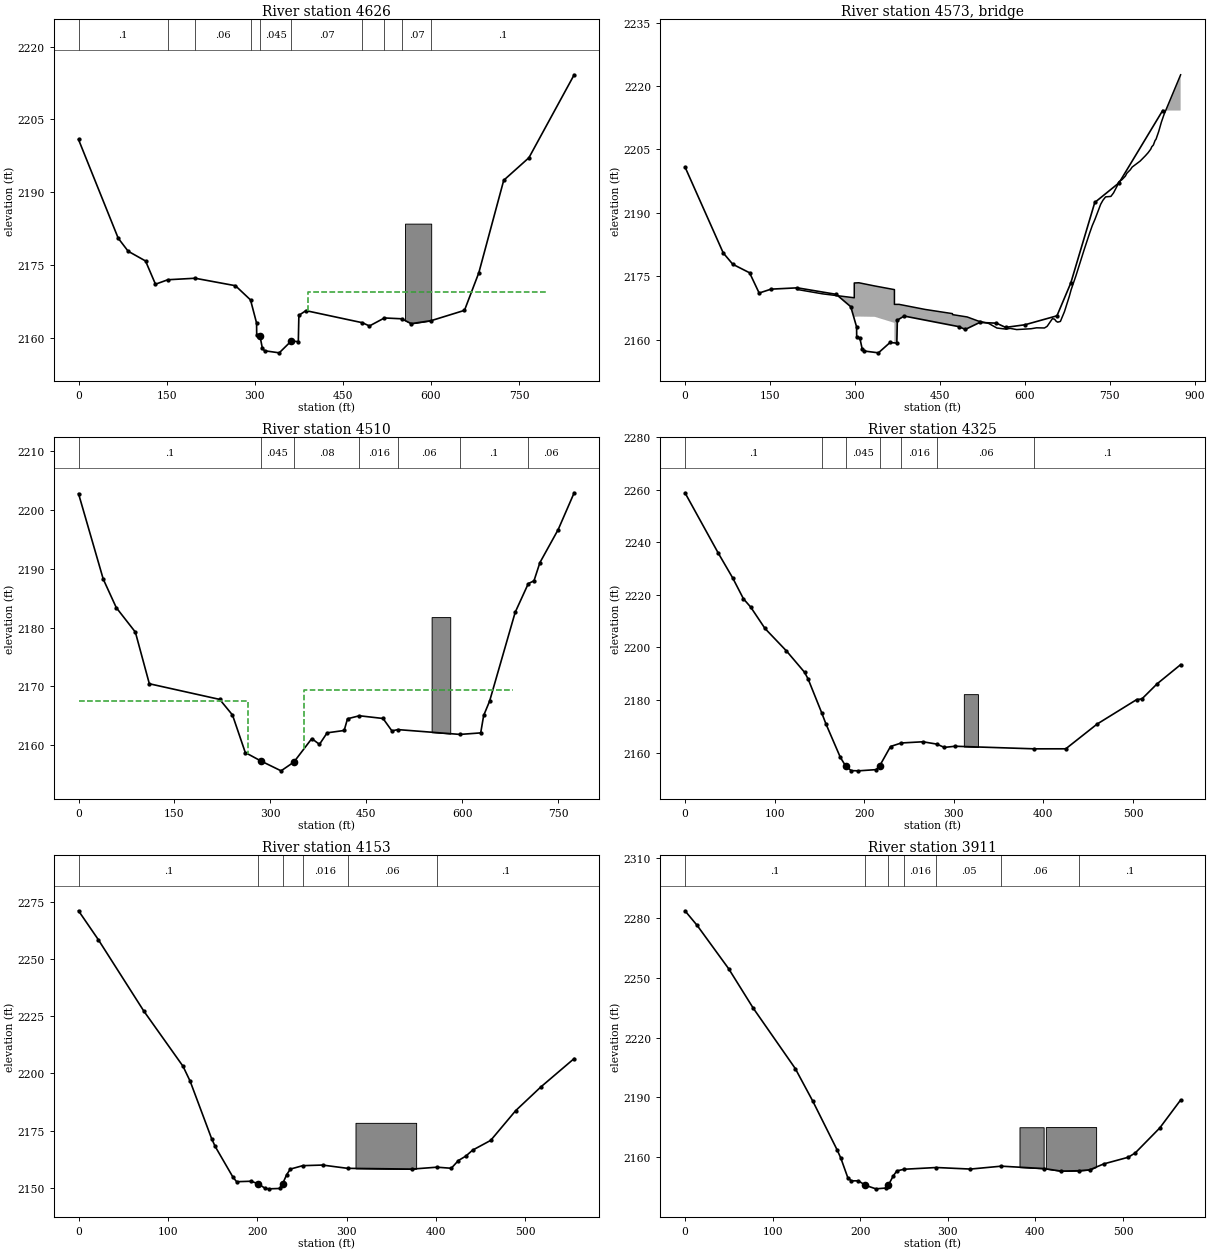
Type RM Length L Ch R = 1 ,4626    ,114.7,115.4,183.8
BEGIN DESCRIPTION:
Structure XS 3; 20.8 ft between structure and xs
END DESCRIPTION:
XS GIS Cut Line= 4
 2217032.2192927436372.3729439172216831.51468398436304.382221677
2216825.26369131435999.0226005572216551.59032505435821.192652237
#Sta/Elev= 30
       0 2200.85    67.6 2180.49    84.5 2177.81   114.1  2175.8     131 2171.01
   152.1 2171.93   198.5 2172.24   267.1  2170.7   292.8 2167.77   303.1    2163
  303.32 2160.49  308.85 2160.34  312.97  2157.8  316.67 2157.29  341.69 2156.86
  362.23 2159.31  374.16 2159.16   375.1 2164.59   387.1 2165.56   483.2 2163.07
   495.2  2162.4   520.7 2164.05   550.1 2163.88   566.3 2162.88   600.4  2163.5
     657 2165.62   681.4 2173.37   723.8 2192.44   766.7 2197.09   843.7 2214.19
#Mann= 10 ,-1,0
       0      .1       0   152.1    .016       0   198.5     .06       0
   292.8     .07       0  308.85    .045       0  362.23     .07       0
   483.2      .1       0   520.7    .016       0   550.1     .07       0
   600.4      .1       0
#XS Ineff= 2 ,-1
       0     279 2167.57     390     800 2169.47
Permanent Ineff=
       F       F
#Block Obstruct= 1 ,-1
  555.79  600.33  2183.5
Bank Sta=308.85,362.23
XS Rating Curve= 0 ,0
Exp/Cntr(USF)=0,0
Exp/Cntr=0.5,0.3

Type RM Length L Ch R = 3 ,4573    ,,,
BEGIN DESCRIPTION:
Seneca Trail
Included survey from Bridge 54075SWA020
Included 3.5 ft rail.
Bridge span: 70.94 ft
Deck thickness: 4.5 ft
END DESCRIPTION:
Bridge Culvert--1,0,-1,-1, 0
Deck Dist Width WeirC Skew NumUp NumDn MinLoCord MaxHiCord MaxSubmerge Is_Ogee
20.7,41.5,2.6,0, 60, 60, , , 0.98, 0, 0,0,,
  199.03  242.84     299     299  307.13  335.28  369.94  369.94  378.16  424.21
   472.4 472.749 498.426 517.583 536.357 551.013 567.242 574.279 585.912 611.452
 620.956  634.92 639.613     649 652.802 655.711 658.387  663.08 670.252 678.977
 681.885  690.61 704.875 714.708 719.402 724.095 734.234 738.175 742.869 752.256
 756.949 763.317 766.336 772.042 777.858 780.416 786.583 789.803 803.884  813.27
 817.964 822.657 824.391 827.351 830.208 832.044 836.738 841.431 846.125 875.443
 2171.83 2170.82 2169.89 2173.39 2173.44 2172.68 2171.82 2168.32 2168.33 2167.13
 2166.142165.8982165.3512164.4062163.819 2162.732162.474 2162.652162.3652162.565
2162.7812162.7422163.125 2164.952164.821 2164.322164.1192164.2942166.6062170.296
2171.7282175.1322181.1972185.1882186.9752188.4372192.0152192.9542193.7592193.871
2194.7042196.3462197.3352197.8592198.6812199.3522200.1752200.8082202.224  2203.5
2204.2032205.051  2205.62206.0352207.0822207.4162209.2462211.4412213.2552222.648
                 2165.38 2165.38 2165.44 2165.38 2163.95 2163.95
                                                                                
                                                                                
                                                                                
                                                                                
                                                                                
   -74.3 -65.218 -61.989  -57.82  -53.62  -49.42 -45.221 -41.021 -36.582 -28.421
 -20.022  -7.947  -3.223    .977   5.177  13.577  17.776  21.976  30.376  38.776
  43.006  47.175  51.375  63.974  71.594  76.574  80.774  84.973  89.173  93.373
  97.573  100.23 106.593 110.172 114.372 118.572 122.772 131.171 135.228 144.773
  172.56  216.37  272.53  272.53  280.66  308.81  343.47  343.47  351.69  397.74
  445.93 446.258 463.616 559.681 574.973 580.952 590.456  604.42 607.761     650
2227.5962223.0292221.5172219.445 2217.152215.2072213.0632211.0252208.9792205.595
2202.8342198.4222196.9812195.4952194.1482190.7632189.2792188.0082185.6492183.747
2182.6192181.6632181.2772179.0832178.1942177.4772177.111 2176.852176.7012176.296
2175.313 2174.412171.8992170.5782170.3132170.5772170.682  2171.52171.6792171.901
 2171.83 2170.82 2169.89 2173.39 2173.44 2172.68 2171.82 2168.32 2168.33 2167.13
 2166.142165.8542165.4732162.4172162.5992162.5652162.7812162.7422163.0132163.013
                                                                                
                                                                                
                                                                                
                                                                                
                 2165.38 2165.38 2165.44 2165.38 2163.95 2163.95
                                                                                
BR Coef=-1 ,-1 , 0 ,, 0 ,,,0.8,0,1,0,
WSPro=,,,, 1 ,,,, 0 ,,,, 0 ,,,,-1 ,-1 ,-1 , 0 , 0 , 0 , 0 , 0
BR U #Sta/Elev= 30
       0 2200.85    67.6 2180.49    84.5 2177.81   114.1  2175.8     131 2171.01
   152.1 2171.93   198.5 2172.24   267.1  2170.7   292.8 2167.77   303.1    2163
  303.32 2160.49  308.85 2160.34  312.97  2157.8  316.67 2157.29  341.69 2156.86
  362.23 2159.31  374.16 2159.16   375.1 2164.59   387.1 2165.56   483.2 2163.07
   495.2  2162.4   520.7 2164.05   550.1 2163.88   566.3 2162.88   600.4  2163.5
     657 2165.62   681.4 2173.37   723.8 2192.44   766.7 2197.09   843.7 2214.19
BR U #Mann= 10
       0      .1   152.1    .016   198.5     .06   292.8     .07  308.85     .04
  362.23     .07   483.2      .1   520.7    .016   550.1     .07   600.4      .1
BR D #Sta/Elev= 30
       0 2202.78   38.74 2188.23   59.12 2183.39   88.92 2179.24   110.8 2170.46
  220.86  2167.8  240.87 2165.15  260.87 2158.77  284.88 2157.36  316.88 2155.66
  336.89 2157.15   364.9 2161.14   376.9 2160.16   388.9 2162.12  415.56 2162.52
   420.8 2164.51  439.32 2165.02  476.36 2164.56  490.25 2162.45  499.51 2162.67
  596.74 2161.85  629.15 2162.11  633.78 2165.07  643.04  2167.5   683.1 2182.61
  703.57 2187.48  712.49 2187.96  721.75 2191.05  750.37 2196.67  775.35 2202.92
BR D #Mann= 7
       0      .1  284.88     .04  336.89     .08  439.32    .016  499.51     .06
  596.74      .1  703.57     .06
BC Design=,, 0 ,, 0 ,,,,,,
BC Use User HTab Curves=0
BC User HTab FreeFlow(D)= 0

Type RM Length L Ch R = 1 ,4510    ,230.7,185.6,76.2
BEGIN DESCRIPTION:
Structure XS 2; 26.3 ft between structure and XS
channel not burned, lidar elevations lower than survey points
END DESCRIPTION:
XS GIS Cut Line= 4
2217025.23182625436310.4052677312216906.95469728436274.375969002
2216900.70370461435982.5293637372216589.86954475435801.321161454
#Sta/Elev= 30
       0 2202.78   38.74 2188.23   59.12 2183.39   88.92 2179.24   110.8 2170.46
  220.86  2167.8  240.87 2165.15  260.87 2158.77  284.88 2157.36  316.88 2155.66
  336.89 2157.15   364.9 2161.14   376.9 2160.16   388.9 2162.12  415.56 2162.52
   420.8 2164.51  439.32 2165.02  476.36 2164.56  490.25 2162.45  499.51 2162.67
  596.74 2161.85  629.15 2162.11  633.78 2165.07  643.04  2167.5   683.1 2182.61
  703.57 2187.48  712.49 2187.96  721.75 2191.05  750.37 2196.67  775.35 2202.92
#Mann= 7 ,-1,0
       0      .1       0  284.88    .045       0  336.89     .08       0
  439.32    .016       0  499.51     .06       0  596.74      .1       0
  703.57     .06       0
#XS Ineff= 2 ,-1
       0     265 2167.57     352  680.11 2169.47
Permanent Ineff=
       F       F
#Block Obstruct= 1 ,-1
  552.36  581.48 2181.79
Bank Sta=284.88,336.89
XS Rating Curve= 0 ,0
Exp/Cntr(USF)=0,0
Exp/Cntr=0.5,0.3

Type RM Length L Ch R = 1 ,4325    ,170.4,171.8,172.3
BEGIN DESCRIPTION:
Structure XS 1
END DESCRIPTION:
XS GIS Cut Line= 3
2217125.47695731435905.7106558922216798.62854765435914.758362733
2216617.67441082435779.042760109
#Sta/Elev= 30
       0 2258.93    37.3 2235.86    53.3 2226.47    65.3 2218.52    73.3 2215.41
    89.3 2207.24   113.3 2198.67   133.4 2190.59   137.4 2188.03   152.6 2175.12
   157.4 2170.83   173.4 2158.16   179.2 2154.94   185.4 2153.11   193.4 2153.02
   213.4 2153.48   217.4 2154.98   229.4 2162.29   241.4 2163.63   265.5 2164.09
   281.1  2163.2   289.4 2161.94   301.4 2162.39     390  2161.4     425 2161.41
     460 2170.84   504.1 2180.15     510 2180.42     527 2186.18   553.2 2193.47
#Mann= 7 ,-1,0
       0      .1       0   152.6     .07       0   179.2    .045       0
   217.4      .1       0   241.4    .016       0   281.1     .06       0
     390      .1       0
#Block Obstruct= 1 ,-1
  311.25  326.97 2182.23
Bank Sta=179.2,217.4
XS Rating Curve= 0 ,0
Exp/Cntr(USF)=0,0
Exp/Cntr=0.3,0.1

Type RM Length L Ch R = 1 ,4153    ,242.7,242.5,242.4
XS GIS Cut Line= 2
2217133.00532235435747.0935338742216578.81600045435729.440834633
#Sta/Elev= 30
       0 2271.14    22.1 2258.54    72.9 2227.36   116.9 2203.13   124.9 2196.57
   148.9 2171.47   152.9 2168.03   172.9 2154.53   176.9 2152.62   192.9 2152.82
201.15912151.735   208.9 2149.66   212.9  2149.5   224.9 2149.66 228.259 2151.66
   232.9 2155.71     237 2158.14   250.9 2159.64     273  2159.9     301 2158.47
     373 2158.14     401 2158.97     417  2158.5     425 2161.89   433.2  2163.8
   440.9 2166.43   461.1 2170.69   489.1 2183.72   517.1 2194.03   554.5 2206.49
#Mann= 6 ,-1,0
       0      .1       0201.1591    .045       0 228.259      .1       0
   250.9    .016       0     301     .06       0     401      .1       0
#Block Obstruct= 1 ,-1
  309.87  377.71 2178.37
Bank Sta=201.1591,228.259
XS Rating Curve= 0 ,0
Exp/Cntr(USF)=0,0
Exp/Cntr=0.3,0.1

Type RM Length L Ch R = 1 ,3911    ,335.7,337.4,335.2
XS GIS Cut Line= 2
2217138.00153067435503.523830914 2216572.3744653435488.847960971
#Sta/Elev= 30
       0 2283.54    13.8 2276.26    49.8 2254.54    77.9 2234.74   125.9 2204.46
   145.9 2188.12   173.9 2163.49   177.9 2159.56   185.9 2149.72   189.9 2148.15
   197.9 2148.19205.90352145.949   217.9 2144.16   229.9 2144.58232.0534 2145.98
   237.9 2150.74   241.9 2153.16   250.1 2153.98     287 2154.85   325.9 2154.07
     361 2155.52     410 2154.31   429.2 2153.06     450 2153.23     462  2153.7
     478 2156.65     506 2159.99     514 2162.16     542 2174.69   565.8 2188.69
#Mann= 7 ,-1,0
       0      .1       0205.9035    .045       0232.0534      .1       0
   250.1    .016       0     287     .05       0     361     .06       0
     450      .1       0
#Block Obstruct= 2 ,-1
  381.85  409.41 2175.04  411.96  469.32 2175.12
Bank Sta=205.9035,232.0534
XS Rating Curve= 0 ,0
Exp/Cntr(USF)=0,0
Exp/Cntr=0.3,0.1

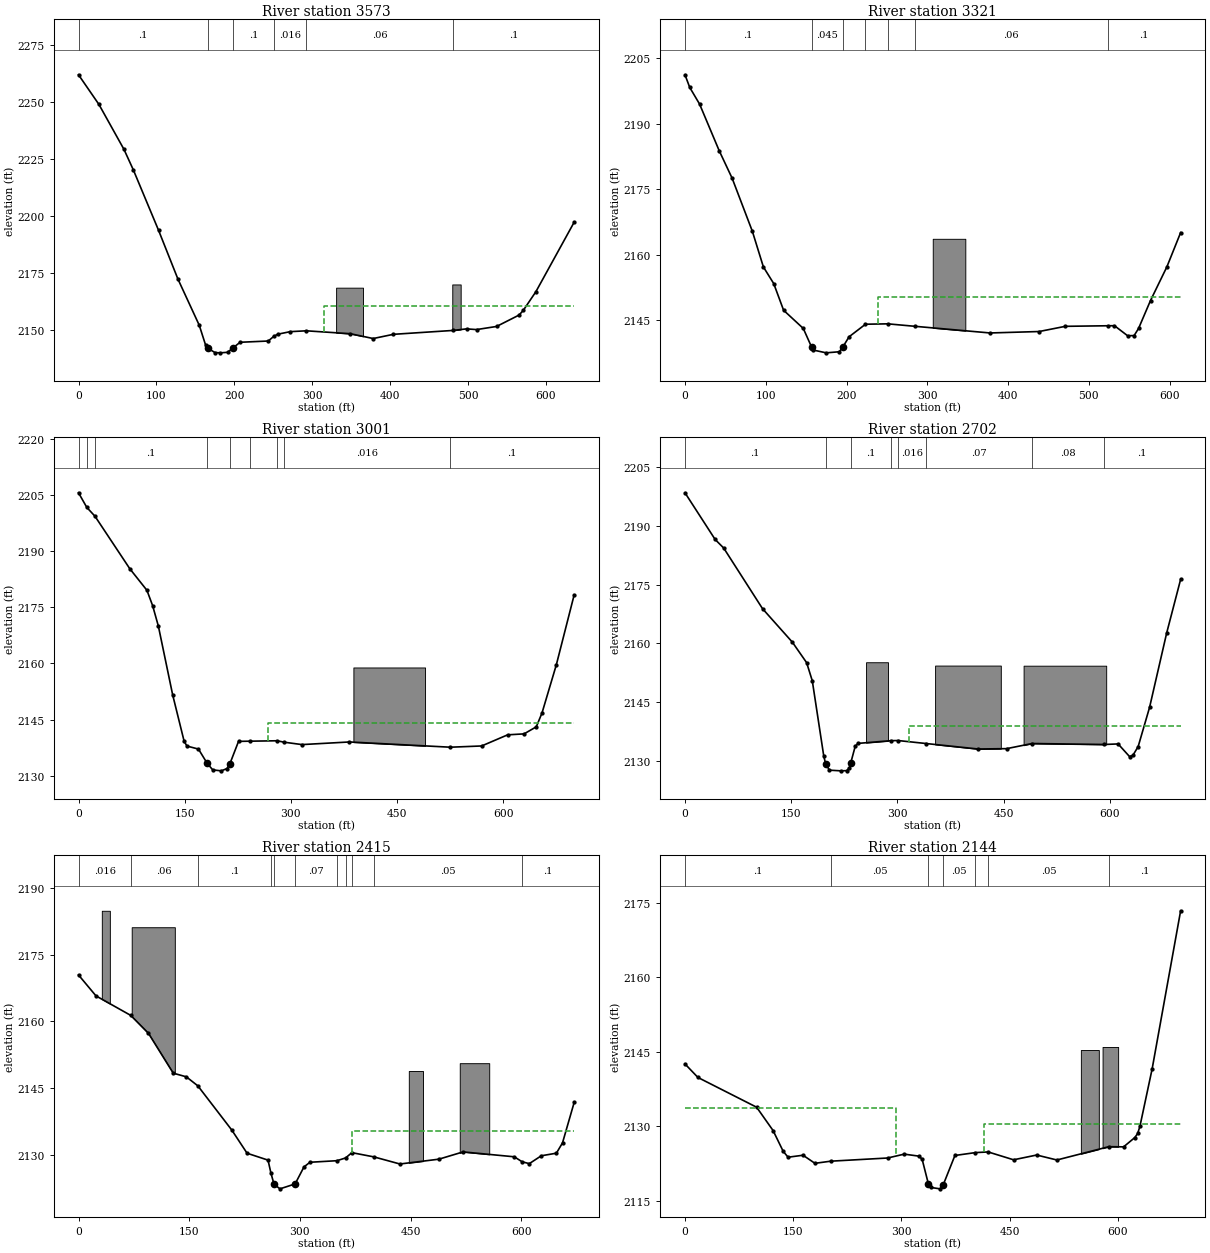
Type RM Length L Ch R = 1 ,3573    ,249.5,252.4,251.3
XS GIS Cut Line= 3
2217146.21286649435192.3989061142216867.89258046435160.634395804
 2216535.1242915435287.512202637
#Sta/Elev= 30
       0 2261.91    26.2  2248.9    58.4 2229.14    70.5 2220.07   102.7  2193.7
   127.6 2172.26     155 2151.97   163.1 2143.32166.00552141.881   175.2 2139.98
   181.8 2139.86   191.3 2140.09198.30542142.017   207.4  2144.5   243.6 2145.05
   250.5 2147.04   255.7 2148.03   271.8 2149.16   292.5 2149.53     349 2148.25
   378.3 2146.14   404.3 2147.99     481  2149.7   498.2 2150.38     511 2150.07
   536.7 2151.44   565.5 2156.43   570.9 2158.46   587.2 2166.72   636.3 2197.21
#Mann= 6 ,-1,0
       0      .1       0166.0055    .045       0198.3054      .1       0
   250.5    .016       0   292.5     .06       0     481      .1       0
#XS Ineff= 2 , 0
                           315.1         2160.52
Permanent Ineff=
       F       F
#Block Obstruct= 2 ,-1
   330.7  365.18 2168.47  479.81  490.61 2169.88
Bank Sta=166.0055,198.3054
XS Rating Curve= 0 ,0
Exp/Cntr(USF)=0,0
Exp/Cntr=0.3,0.1

Type RM Length L Ch R = 1 ,3321    ,318.8,319.8,316.7
XS GIS Cut Line= 3
2217091.35047694435029.7073453762217050.04621713434934.265923821
2216547.31817872434849.959049145
#Sta/Elev= 30
       0  2201.2     5.9  2198.3    18.1 2194.48    42.4  2183.8    58.4 2177.51
    83.4 2165.38    97.1  2157.2   109.9 2153.39   122.1 2147.29   146.5 2143.12
  156.772138.863   158.6 2138.19   174.8 2137.54   191.1 2137.79   195.1 2138.77
   203.2 2141.22   223.5 2144.09   251.1 2144.18   284.4 2143.62   377.8 2142.09
   438.5 2142.42   470.9 2143.61   523.4 2143.74   531.8 2143.75     548 2141.46
   556.1 2141.49   561.6 2143.12   576.4 2149.52   596.7 2157.24   613.7 2165.07
#Mann= 7 ,-1,0
       0      .1       0  156.77    .045       0   195.1      .1       0
   223.5    .016       0   251.1     .07       0   284.4     .06       0
   523.4      .1       0
#XS Ineff= 2 , 0
                          239.38         2150.26
Permanent Ineff=
       F       F
#Block Obstruct= 1 ,-1
  306.78   347.1 2163.65
Bank Sta=156.77,195.1
XS Rating Curve= 0 ,0
Exp/Cntr(USF)=0,0
Exp/Cntr=0.3,0.1

Type RM Length L Ch R = 1 ,3001    ,301.1,299.2,299.9
XS GIS Cut Line= 2
2217247.75407145434643.9496989742216555.26544977434541.677958772
#Sta/Elev= 30
       0 2205.64    11.7 2201.73    23.2 2199.38    72.4 2185.34    96.6 2179.57
   104.7 2175.45   112.8 2169.97     133 2151.58   149.2 2139.17   153.2 2137.91
   169.4 2137.11   181.7  2133.3   189.6 2131.54   201.7 2131.29   209.8 2131.91
   213.9 2133.24     226 2139.17   242.2 2139.22   280.4 2139.33   290.7 2138.94
   315.6 2138.31   382.6 2139.01   525.2 2137.61   569.3 2137.94   606.1 2140.92
   629.2 2141.17   646.5 2143.06   654.6 2146.77   674.8 2159.63     700 2178.34
#Mann= 9 ,-1,0
       0      .1       0    11.7    .016       0    23.2      .1       0
   181.7    .045       0   213.9      .1       0   242.2    .016       0
   280.4      .1       0   290.7    .016       0   525.2      .1       0
#XS Ineff= 2 , 0
                          266.99         2143.97
Permanent Ineff=
       F       F
#Block Obstruct= 1 ,-1
  388.21  489.41 2158.93
Bank Sta=181.7,213.9
XS Rating Curve= 0 ,0
Exp/Cntr(USF)=0,0
Exp/Cntr=0.3,0.1

Type RM Length L Ch R = 1 ,2702    ,294,287.1,282.8
XS GIS Cut Line= 2
2217358.39541856434358.2559551652216664.66996183 434264.74130018
#Sta/Elev= 30
       0 2198.42    42.6 2186.51    54.7 2184.32   109.6 2168.84   151.6 2160.33
   171.8 2155.09   179.8 2150.47     196 2131.27  198.622129.313     204 2127.67
   220.2  2127.5   228.3 2127.55   232.3 2128.25   234.1 2129.51   240.4 2133.75
   244.4  2134.5   290.6 2135.19   300.9 2135.23   340.8 2134.46   413.9 2133.07
   454.3 2133.16   490.2 2134.47   591.5 2134.22   611.7 2134.36   627.8 2131.15
   632.5 2131.43     640 2133.68   656.1 2143.67   680.3 2162.67     700 2176.34
#Mann= 8 ,-1,0
       0      .1       0  198.62    .045       0   234.1      .1       0
   290.6     .07       0   300.9    .016       0   340.8     .07       0
   490.2     .08       0   591.5      .1       0
#XS Ineff= 2 , 0
                          316.28         2139.04
Permanent Ineff=
       F       F
#Block Obstruct= 3 ,-1
  255.73  286.69  2155.2  353.22  446.04 2154.35  478.22  594.87 2154.32
Bank Sta=198.62,234.1
XS Rating Curve= 0 ,0
Exp/Cntr(USF)=0,0
Exp/Cntr=0.3,0.1

Type RM Length L Ch R = 1 ,2415    ,266.1,271,288.4
XS GIS Cut Line= 4
2217418.85315425434096.9215201522217209.16824559434032.835339677
2217043.77940376434060.9844692432216764.56585209434006.249764916
#Sta/Elev= 30
       0 2170.42    23.7 2165.71    70.7 2161.33    94.8 2157.28   128.3 2148.33
   146.1  2147.5   161.7 2145.47   207.8  2135.5   228.4 2130.31   256.8 2128.76
   260.8 2125.79   264.9 2123.34     273  2122.3293.50342123.408   305.5 2127.23
   313.6 2128.28   350.1 2128.63   361.9 2129.25   370.4 2130.44   400.2 2129.49
   435.5 2127.89   488.2 2128.97   521.1 2130.61   590.4 2129.51   601.2 2128.38
   610.8 2127.97   627.1 2129.74   647.5 2130.32   655.8 2132.64   671.6 2141.74
#Mann= 11 ,-1,0
       0    .016       0    70.7     .06       0   161.7      .1       0
   260.8     .07       0   264.9    .045       0293.5034     .07       0
   350.1    .016       0   361.9      .1       0   370.4    .016       0
   400.2     .05       0   601.2      .1       0
#XS Ineff= 2 , 0
                          370.38         2135.23
Permanent Ineff=
       F       F
#Block Obstruct= 4 ,-1
   31.58   42.46 2184.86   72.08   130.5 2181.16  447.54  466.77 2148.81
  516.57   556.5 2150.57
Bank Sta=264.9,293.5034
XS Rating Curve= 0 ,0
Exp/Cntr(USF)=0,0
Exp/Cntr=0.3,0.1

Type RM Length L Ch R = 1 ,2144    ,205.5,197.4,197.9
XS GIS Cut Line= 4
2217396.49780628433934.1229024872217318.87169105433832.654825806
2217042.05229528433761.9141860812216768.71562531433767.194791517
#Sta/Elev= 30
       0 2142.51      18 2139.78    99.3 2133.79   122.1 2129.09   136.1 2124.91
   142.9 2123.72   163.6 2124.12   180.1 2122.49   201.9 2122.92   280.8 2123.56
   303.8 2124.34   324.6 2123.93   328.7 2123.29   337.4  2118.3   341.1 2117.62
   353.5 2117.35   357.6 2118.05   374.1 2124.07   402.5 2124.65   420.2 2124.78
   455.4  2123.2   487.4 2124.16   515.4 2123.16   587.3 2125.84   607.9 2125.81
   623.4 2127.68   627.4 2128.51   630.5 2129.96   647.4  2141.5   686.9 2173.36
#Mann= 7 ,-1,0
       0      .1       0   201.9     .05       0   337.4    .045       0
   357.6     .05       0   402.5    .016       0   420.2     .05       0
   587.3      .1       0
#XS Ineff= 2 , 0
          292.77 2133.73  414.08         2130.33
Permanent Ineff=
       F       F
#Block Obstruct= 2 ,-1
  548.64  573.53 2145.31  578.72  600.28 2145.93
Bank Sta=337.4,357.6
XS Rating Curve= 0 ,0
Exp/Cntr(USF)=0,0
Exp/Cntr=0.3,0.1

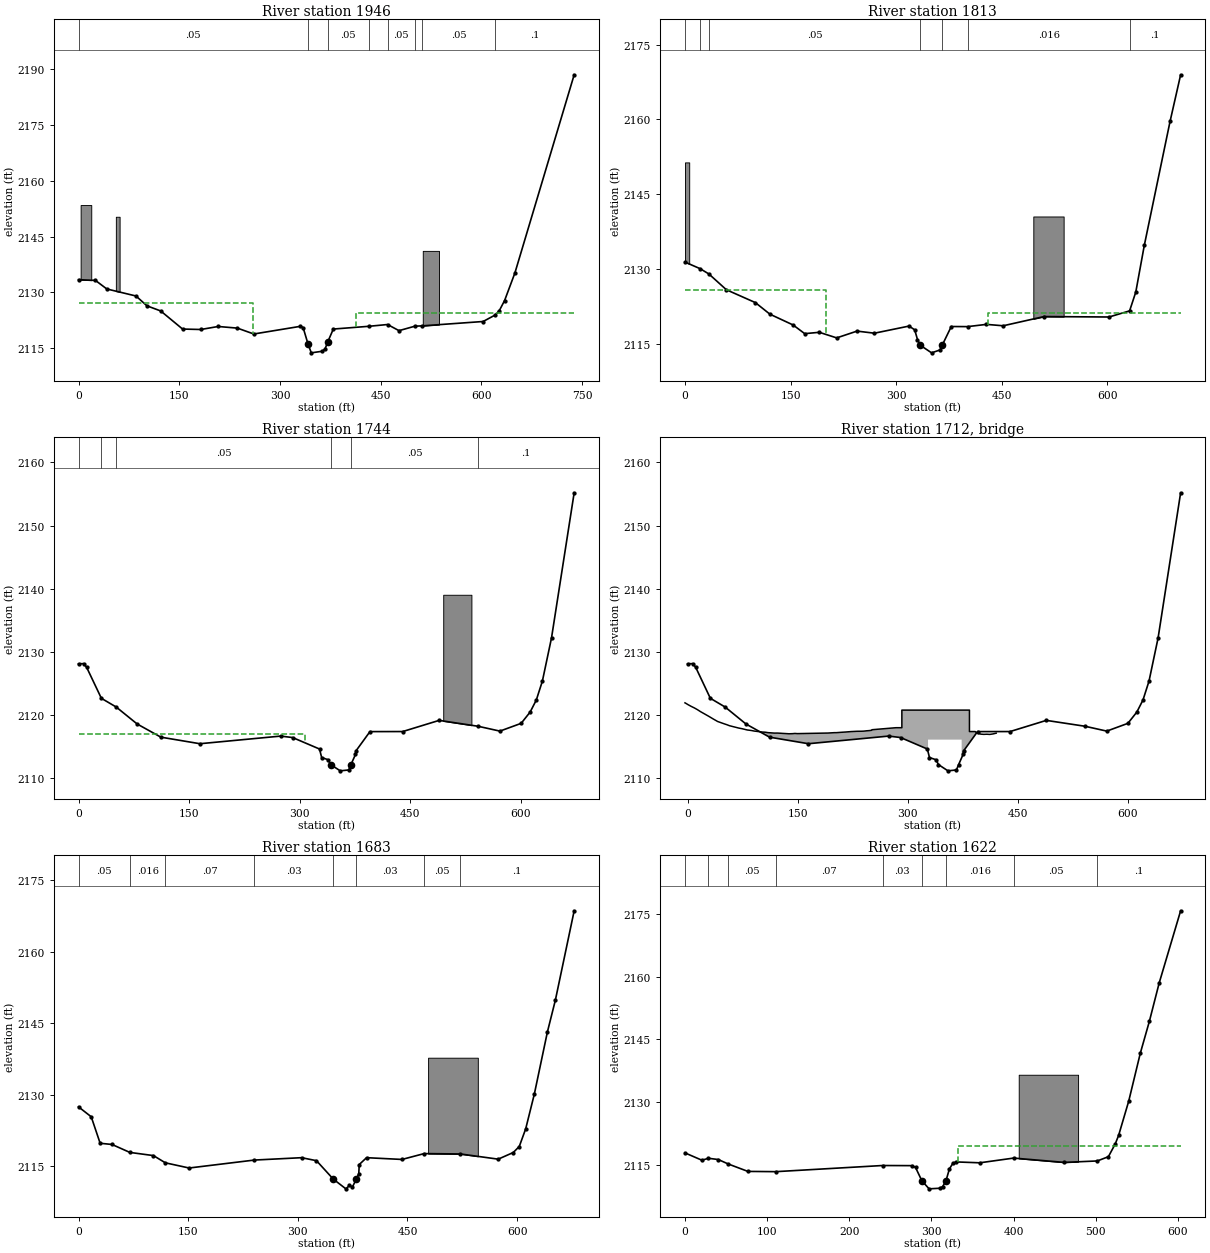
Type RM Length L Ch R = 1 ,1946    ,143.9,133.5,124.7
XS GIS Cut Line= 4
2217495.41367454433690.9632686632217452.12989181433647.679485933
2216985.78203917433554.1306651942216784.72188714 433565.30067364
#Sta/Elev= 30
       0 2133.44    25.2 2133.25    42.1 2130.95    85.6 2129.05     102  2126.4
   122.4 2125.03     155 2120.16   182.2 2120.04     208 2120.85   236.6 2120.41
   261.1 2118.83   330.4 2120.89   334.5 2120.57   341.9 2116.09   346.7 2113.76
   363.1 2114.19   367.1 2114.77   371.2 2116.71   379.5 2120.16   432.4  2120.9
   460.3 2121.38   477.3 2119.73     501 2120.93   511.8 2121.02   602.6 2122.19
   620.2  2123.9   626.6 2125.08   634.6 2127.84   649.9 2135.23   738.2 2188.57
#Mann= 8 ,-1,0
       0     .05       0   341.9    .045       0   371.2     .05       0
   432.4    .016       0   460.3     .05       0     501    .016       0
   511.8     .05       0   620.2      .1       0
#XS Ineff= 2 , 0
          260.24 2127.17  413.08         2124.44
Permanent Ineff=
       F       F
#Block Obstruct= 3 ,-1
    3.16   18.98 2153.52   55.61   61.21 2150.37  512.72  536.85 2141.19
Bank Sta=341.9,371.2
XS Rating Curve= 0 ,0
Exp/Cntr(USF)=0,0
Exp/Cntr=0.3,0.1

Type RM Length L Ch R = 1 ,1813    ,69.5,68.9,74.5
BEGIN DESCRIPTION:
Structure XS 4
END DESCRIPTION:
XS GIS Cut Line= 4
2217517.16480822433531.9314733962217219.47498766433456.918760744
 2217137.0017237433458.711657787 2216830.0188118433389.900603541
#Sta/Elev= 30
       0 2131.37    21.6 2130.04      34 2128.98    58.8 2125.82     100 2123.24
   120.6 2120.92   153.6 2118.75   170.1 2117.01   190.8 2117.28   215.5 2116.16
   244.4 2117.52   269.1  2117.1   318.3 2118.53   326.3 2117.78   330.3 2115.83
   334.3 2114.68   350.3 2113.16   362.3 2113.74   365.3 2114.66   378.3 2118.44
   401.5 2118.42   428.3 2118.87     452 2118.59   510.1 2120.44   602.4 2120.35
   631.6 2121.58   640.4 2125.36   652.5 2134.73   689.1 2159.61   704.1 2168.95
#Mann= 7 ,-1,0
       0     .07       0    21.6    .016       0      34     .05       0
   334.3    .045       0   365.3     .03       0   401.5    .016       0
   631.6      .1       0
#XS Ineff= 2 , 0
          199.66  2125.8  430.76         2121.17
Permanent Ineff=
       F       F
#Block Obstruct= 2 ,-1
       0    6.01 2151.37  494.82   537.9 2140.52
Bank Sta=334.3,365.3
XS Rating Curve= 0 ,0
Exp/Cntr(USF)=0,0
Exp/Cntr=0.5,0.3

Type RM Length L Ch R = 1 ,1744    ,61.9,61.1,60.6
BEGIN DESCRIPTION:
Structure XS 3; 21.2 ft between structure and xs
END DESCRIPTION:
XS GIS Cut Line= 5
2217531.17897284 433368.18043913 2217460.9109444433371.804495467
 2217284.5434234433403.4150356982217091.49555357 433377.17551941
2216870.33391628433322.822235671
#Sta/Elev= 30
       0 2128.07       7  2128.1      11 2127.52      31  2122.6    51.1 2121.22
    79.5 2118.53   111.7 2116.44   164.6  2115.4   274.1 2116.61   290.3 2116.38
   326.8 2114.56  329.71 2113.21  338.57 2112.86  341.98 2112.09  354.87  2111.1
  366.48 2111.24  369.31 2112.06  375.57  2113.7   376.2 2114.26   395.2 2117.32
   439.6 2117.33     489  2119.1   541.7 2118.17   571.4  2117.4   600.2 2118.63
   612.4 2120.42   620.8 2122.34     629 2125.33   641.4 2132.19   672.1 2155.19
#Mann= 6 ,-1,0
       0     .05       0      31    .016       0    51.1     .05       0
  341.98    .045       0  369.31     .05       0   541.7      .1       0
#XS Ineff= 2 ,-1
       0  306.54 2116.94   394.8   608.7 2116.98
Permanent Ineff=
       F       F
#Block Obstruct= 1 ,-1
  494.54  532.77 2139.02
Bank Sta=341.98,369.31
XS Rating Curve= 0 ,0
Exp/Cntr(USF)=0,0
Exp/Cntr=0.5,0.3

Type RM Length L Ch R = 3 ,1712    ,,,
BEGIN DESCRIPTION:
Old Buckeye Road
Included survey from Bridge 54075SWA010
Bridge span: 46 ft
Deck thickness: 2.2 ft
END DESCRIPTION:
Bridge Culvert--1,0,-1,-1, 0
Deck Dist Width WeirC Skew NumUp NumDn MinLoCord MaxHiCord MaxSubmerge Is_Ogee
21.97771,24.8,2.6,0, 172, 111, , , 0.98, 0, ,0,,
    -3.6  -3.295  -3.132    .428    .707   4.709   8.711   9.278  12.057  13.415
  15.933  16.716  17.551  21.688  23.685   24.72  25.825  27.561  28.722  29.961
  31.437  32.724  34.098  35.313  36.726  38.235  39.189  40.589   40.73  42.084
  43.707  44.787  45.555  48.588  48.844  49.026  50.104  52.496  53.468  55.967
  56.957  61.013  62.908  63.229   65.07  66.379   68.11  69.849  72.991  73.183
   73.32  74.131   77.24  77.871  80.261  81.296  82.752  83.732  85.353  87.203
  87.632   89.41  90.673  92.513  93.466  97.523  98.159 101.085 101.579 102.274
 105.636 107.155 108.027 109.693 111.497 112.035 113.749 114.968 116.916 117.806
 118.439 121.797 121.862 121.909 122.187  125.38 125.919 126.677 128.851 129.976
 131.558 132.321 134.032 135.792 136.438 138.089 141.319 142.145 142.733   146.2
 146.204 149.674 191.322 194.269 194.793 194.881 195.006 198.938 199.886 201.734
 202.995 207.051 208.826 209.481 211.077 215.078 216.883 217.265  219.08     221
 221.157 223.082 225.049 225.118 227.083 228.941 229.235 231.085 232.833 233.353
  234.33 235.088 236.619 237.652 239.101 240.339 242.007 243.113 244.058 246.362
 247.126 247.778 250.717   251.3  284.02  292.06  292.06  327.74   373.6  384.21
  384.21  392.04 393.932   395.5 395.731 396.041 399.025 399.774 400.781  402.55
 403.817 406.074  407.86 409.599 411.903 413.124 413.259 415.254 416.445 418.312
 420.109 420.683
2121.8832121.8672121.8562121.6012121.5852121.3312121.108 2121.072120.8932120.798
2120.5992120.5442120.4882120.222 2120.082120.0152119.9412119.8312119.7532119.665
 2119.562119.4692119.3822119.2962119.2072119.1012119.0412118.9412118.9322118.875
2118.7922118.7432118.7112118.6012118.5912118.5832118.5452118.4562118.4162118.304
2118.2592118.1392118.0762118.0672118.0082117.9762117.9262117.8782117.8142117.809
2117.8052117.7832117.6882117.6732117.6022117.5812117.563 2117.552117.5292117.491
2117.4792117.4382117.4082117.3822117.363 2117.312117.3032117.256 2117.252117.247
2117.2292117.2012117.1882117.1562117.1422117.1432117.1342117.1232117.0972117.088
2117.0842117.0932117.0932117.0922117.0912117.0672117.063 2117.062117.0442117.041
2117.0252117.015    21172116.9912116.9872116.9792116.987 2116.992116.9932117.031
2117.0312117.0022117.094 2117.122117.1232117.1232117.125 2117.152117.1532117.151
2117.1562117.2022117.2072117.2122117.2192117.2542117.2742117.2772117.2982117.313
2117.3142117.3282117.3432117.3442117.3592117.3662117.3662117.3722117.3712117.371
 2117.372117.3692117.3742117.3812117.3862117.3992117.4252117.4382117.4492117.466
2117.4742117.4842117.528 2117.62 2117.94 2117.94 2120.73 2120.73 2120.73 2120.73
 2117.33 2117.332117.1182117.0652117.0562117.0462116.9432116.918 2116.912116.892
2116.8842116.8962116.9062116.8952116.8762116.8962116.8982116.9352116.9562117.008
2117.0562117.074
                                                                                
                                                                                
                                                                                
                                                                                
                                                                                
                                                                                
                                                                                
                                                                                
                                                                                
                                                                                
                                                                                
                                                                                
                                                                                
                                                                                
                                                         2116.05 2116.05
                                                                                
                                                                                
                
  48.125  49.079  50.479   50.62  51.974  53.597  54.677  55.445  58.478  58.734
  58.916  59.994  62.386  63.358  65.857  66.847  70.903  72.798  73.119   74.96
  76.269      78  79.739  82.881  83.073   83.21  84.021   87.13  87.761  90.151
  91.186  92.642  93.622  95.243  97.093  97.522    99.3 100.563 102.403 103.356
 107.413 108.049 110.975 111.469 112.164 115.526 117.045 117.917 119.583 121.387
 121.925 123.639 124.858 126.806 127.696 128.329 131.687 131.752 131.799 132.077
  135.27 135.809 136.567 138.741 139.866 141.448 142.211 143.922 145.682 146.328
 147.979 151.209 152.035 152.623  156.09 156.094 159.564 201.212 204.159 204.683
  244.22 244.978 246.509 247.542 248.991 250.229 251.897 253.003 253.948 256.252
 257.016 257.668 260.607  261.19  293.91  301.74  301.74  331.95  337.63  383.49
  394.01  394.01  401.93 403.822  405.39 405.621 405.931 408.915 409.664 410.671
  412.44
2119.1012119.0412118.9412118.9322118.8752118.7922118.7432118.7112118.6012118.591
2118.5832118.5452118.4562118.4162118.3042118.2592118.1392118.0762118.0672118.008
2117.9762117.9262117.8782117.8142117.8092117.8052117.7832117.6882117.6732117.602
2117.5812117.563 2117.552117.5292117.4912117.4792117.4382117.4082117.3822117.363
 2117.312117.3032117.256 2117.252117.2472117.2292117.2012117.1882117.1562117.142
2117.1432117.1342117.1232117.0972117.0882117.0842117.0932117.0932117.0922117.091
2117.0672117.063 2117.062117.0442117.0412117.0252117.015    21172116.9912116.987
2116.9792116.987 2116.992116.9932117.0312117.0312117.0022117.094 2117.122117.123
 2117.372117.3692117.3742117.3812117.3862117.3992117.4252117.4382117.4492117.466
2117.4742117.4842117.528 2117.62 2117.94 2117.94 2120.44 2120.73 2120.73 2120.73
 2120.73 2117.33 2117.332117.1182117.0652117.0562117.0462116.9432116.918 2116.91
2116.892
                                                                                
                                                                                
                                                                                
                                                                                
                                                                                
                                                                                
                                                                                
                                                                                
                                                                                
                                                                 2116.05 2116.05
                                                                                
        
BR Coef=-1 ,-1 , 0 ,, 0 ,,,0.8,0,1,0,
WSPro=,,,, 1 ,,,, 0 ,,,, 0 ,,,,-1 ,-1 ,-1 , 0 , 0 , 0 , 0 , 0
BC Design=,, 0 ,, 0 ,,,,,,
BC Use User HTab Curves=0
BC User HTab FreeFlow(D)= 0

Type RM Length L Ch R = 1 ,1683    ,64.2,60.4,62.9
BEGIN DESCRIPTION:
Structure XS 2; 16.9 ft between structure and xs
END DESCRIPTION:
XS GIS Cut Line= 4
2217537.36267639433300.2718390492217285.48054898433342.501872887
2217092.43267915433316.2623565992216871.27104187 433261.90907286
#Sta/Elev= 30
       0 2127.41    17.4 2125.32    29.6 2119.75    45.8  2119.5    70.2 2117.83
   102.5 2117.16   118.8 2115.64   151.3 2114.55   240.5 2116.22   305.2 2116.72
   325.5 2116.09  348.48 2112.22  365.71 2110.17  370.66 2110.88  374.67 2110.55
  380.09 2112.24  383.37 2113.34     384 2115.28     394 2116.72   442.5 2116.35
   472.8 2117.58   522.4  2117.5   574.1 2116.41   594.7 2117.81   602.9 2119.07
   611.7 2122.79   623.5 2130.08   641.4 2143.16   652.3 2149.85     678 2168.63
#Mann= 8 ,-1,0
       0     .05       0    70.2    .016       0   118.8     .07       0
   240.5     .03       0  348.48    .045       0  380.09     .03       0
   472.8     .05       0   522.4      .1       0
#XS Ineff= 2 ,-1
       0  332.03  2114.7  389.09     650  2114.7
Permanent Ineff=
       F       F
#Block Obstruct= 1 ,-1
  478.18  546.21 2137.74
Bank Sta=348.48,380.09
XS Rating Curve= 0 ,0
Exp/Cntr(USF)=0,0
Exp/Cntr=0.5,0.3

Type RM Length L Ch R = 1 ,1622    ,82.4,83.8,84.2
BEGIN DESCRIPTION:
Structure XS 1
END DESCRIPTION:
XS GIS Cut Line= 3
2217480.71763723433291.5167651572217327.11845036433302.647141017
2216890.80771664433195.795532759
#Sta/Elev= 30
       0 2117.84    20.6 2116.09    28.6 2116.55    40.6 2116.25    52.7 2115.18
    76.6 2113.41   110.5 2113.35   240.4 2114.82   276.5 2114.79   280.6 2114.35
  288.28 2111.17   297.1 2109.24   309.8 2109.38   313.5 2109.75   317.6 2111.15
   321.8    2114   325.9 2115.31     330 2115.68   358.8 2115.47     400  2116.6
   461.4 2115.57   501.7 2115.91   515.3 2116.93   523.6 2119.98   527.7 2122.01
     540 2130.21   554.1 2141.67   565.1 2149.28   577.1  2158.5   603.2 2175.77
#Mann= 9 ,-1,0
       0     .05       0    28.6     .02       0    52.7     .05       0
   110.5     .07       0   240.4     .03       0  288.28    .045       0
   317.6    .016       0     400     .05       0   501.7      .1       0
#XS Ineff= 2 , 0
                          332.85         2119.56
Permanent Ineff=
       F       F
#Block Obstruct= 1 ,-1
  406.16  478.39 2136.54
Bank Sta=288.28,317.6
XS Rating Curve= 0 ,0
Exp/Cntr(USF)=0,0
Exp/Cntr=0.3,0.1