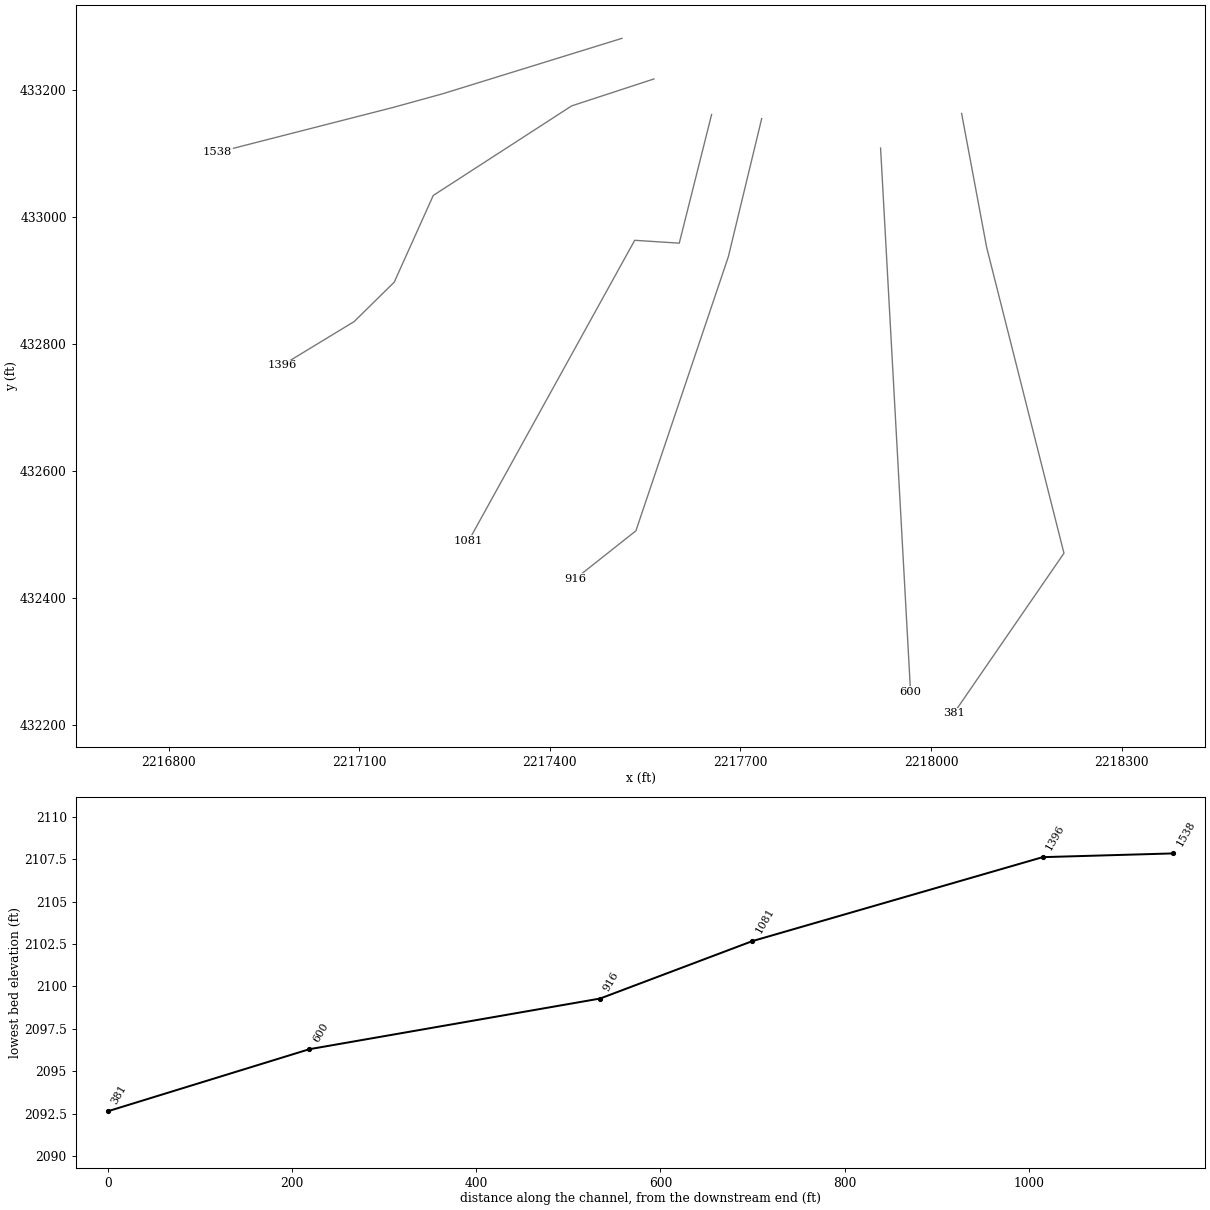
HEC-RAS study SWAGOCK.prj: SWAGOCK

--- SWAGOCK.g01 (geometry) --- (continued)

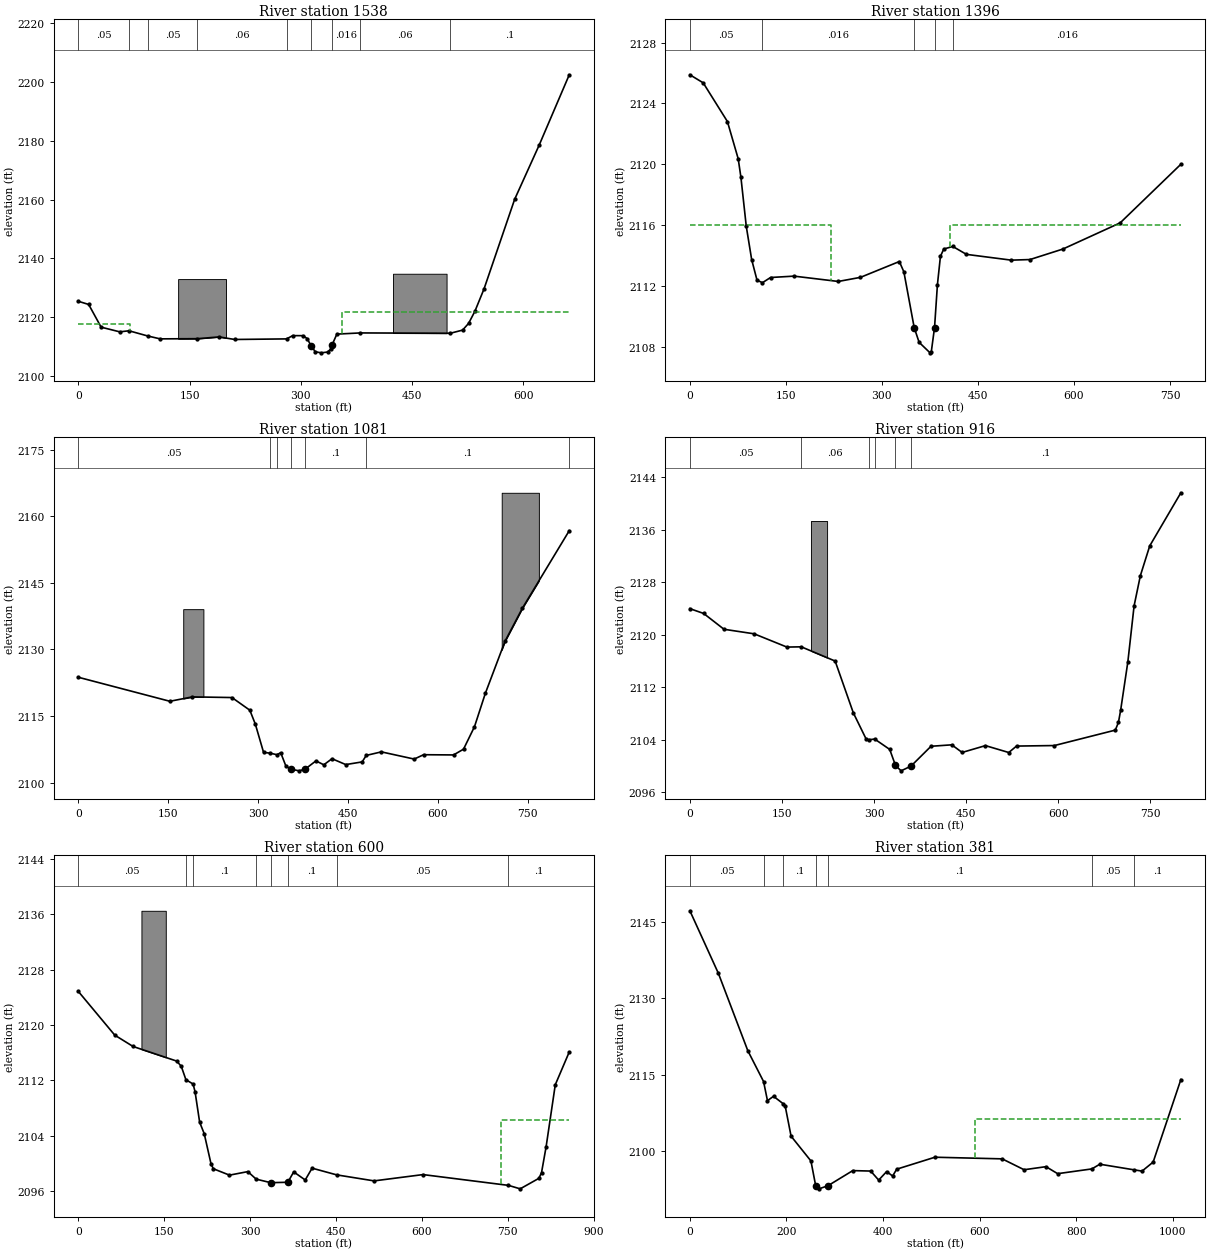
Type RM Length L Ch R = 1 ,1538    ,113,142,148.5
XS GIS Cut Line= 4
 2217513.5592103433281.3160670432217232.02526695433194.259344008
 2217154.0342456433172.7445794972216876.81868565433101.820469521
#Sta/Elev= 30
       0 2125.39      14 2124.31    30.8 2116.57    55.9 2114.98    68.4 2115.34
    93.6 2113.57   110.3 2112.59   160.6 2112.65   189.9 2113.25   210.8 2112.38
   280.7 2112.58     289 2113.69   302.8 2113.68   308.5 2112.68   313.8 2110.21
   319.4  2108.2   327.3 2107.83     336  2108.1   340.2 2109.14  341.74 2110.35
   348.5 2114.21     380 2114.61   501.4  2114.5   517.9 2115.57   526.1 2117.88
   534.6 2122.03   546.8 2129.58   588.1 2160.12   621.1 2178.55   661.7 2202.53
#Mann= 9 ,-1,0
       0     .05       0    68.4    .016       0    93.6     .05       0
   160.6     .06       0   280.7     .03       0   313.8    .045       0
  341.74    .016       0     380     .06       0   501.4      .1       0
#XS Ineff= 2 , 0
           70.06 2117.69  355.81         2121.66
Permanent Ineff=
       F       F
#Block Obstruct= 2 ,-1
  134.57   199.1 2132.95  424.18  496.35 2134.77
Bank Sta=313.8,341.74
XS Rating Curve= 0 ,0
Exp/Cntr(USF)=0,0
Exp/Cntr=0.3,0.1

Type RM Length L Ch R = 1 ,1396    ,258.2,315.3,346.3
BEGIN DESCRIPTION:
Road
END DESCRIPTION:
XS GIS Cut Line= 6
2217563.89772368433217.4318422352217434.34258145  433174.9894606
2217216.55671681433034.0340702572217155.15309207432897.605016889
 2217092.0215614432835.5408239432216979.14823748 432766.95399682
#Sta/Elev= 30
       0 2125.88    20.8 2125.35    58.6 2122.81    75.5 2120.36    79.7 2119.15
    88.1 2115.92    96.5 2113.74   104.9 2112.38   113.4 2112.22     126 2112.56
   162.7 2112.65   231.8  2112.3   266.5 2112.57   327.2 2113.61   334.3 2112.93
   350.4 2109.27   358.1  2108.3   375.2 2107.61   377.1 2107.67   382.2 2109.27
   386.7 2112.09   391.4 2113.95   396.6 2114.43   410.7  2114.6     432 2114.08
   502.1  2113.7   531.3 2113.74   582.7 2114.43   672.2 2116.15     767    2120
#Mann= 5 ,-1,0
       0     .05       0   113.4    .016       0   350.4    .045       0
   382.2     .08       0   410.7    .016       0
#XS Ineff= 2 , 0
             220    2116  406.54         2116.03
Permanent Ineff=
       F       F
Bank Sta=350.4,382.2
XS Rating Curve= 0 ,0
Exp/Cntr(USF)=0,0
Exp/Cntr=0.3,0.1

Type RM Length L Ch R = 1 ,1081    ,159.6,165.4,190.6
Node Name=A
XS GIS Cut Line= 4
2217654.59262203433161.4081395592217603.69927105432958.965698977
2217533.57954303432963.4895523982217272.32700798432490.746869924
#Sta/Elev= 30
       0 2123.74   152.8 2118.33   190.4 2119.32   256.4 2119.17   286.2 2116.32
   295.4 2113.18   309.1 2106.83     320 2106.65   331.5  2106.3   337.7 2106.75
   346.5  2103.7   354.8 2103.04   368.5 2102.67  378.81 2103.09   396.5 2104.91
   409.6 2104.03   423.3  2105.4   446.2 2104.08   473.6 2104.68   480.4 2106.14
   505.6 2106.94   560.4 2105.32   576.1  2106.3   626.1 2106.25   642.7 2107.55
     661 2112.61   679.1 2120.12   711.9 2131.83   740.9 2139.28   819.1 2156.74
#Mann= 7 ,-1,0
       0     .05       0     320    .016       0   331.5     .05       0
   354.8    .045       0  378.81      .1       0   480.4      .1       0
   819.1     .06       0
#Block Obstruct= 2 ,-1
  175.07  208.74 2139.07  706.41  768.42 2165.27
Bank Sta=354.8,378.81
XS Rating Curve= 0 ,0
Exp/Cntr(USF)=0,0
Exp/Cntr=0.3,0.1

Type RM Length L Ch R = 1 ,916     ,297.8,315.7,370.2
XS GIS Cut Line= 4
2217733.41333036433154.9783090642217680.94754446432937.663621588
2217535.49501071432506.3221598652217440.41271908432431.049615424
#Sta/Elev= 30
       0 2123.98    22.4 2123.25    55.6 2120.84   104.7 2120.15   158.1 2118.13
   181.5 2118.17   236.7    2116   266.3 2108.12   287.4 2104.09   291.6 2104.02
   301.1 2104.13   325.6 2102.55     335 2100.12   344.1 2099.29   360.3 2100.01
   392.9 2103.03   426.7 2103.25   443.6 2102.09   481.6 2103.13   519.6 2102.08
   532.2 2103.06   593.9 2103.14   693.2 2105.49   698.3 2106.67   701.9 2108.53
   713.6 2115.87   723.8 2124.41     734    2129   749.3 2133.54     800 2141.62
#Mann= 6 ,-1,0
       0     .05       0   181.5     .06       0   291.6    .016       0
   301.1      .1       0     335    .045       0   360.3      .1       0
#Block Obstruct= 1 ,-1
  197.25  223.56 2137.32
Bank Sta=335,360.3
XS Rating Curve= 0 ,0
Exp/Cntr(USF)=0,0
Exp/Cntr=0.3,0.1

Type RM Length L Ch R = 1 ,600     ,192.7,218.8,262.4
XS GIS Cut Line= 2
2217920.50821987433108.754844976 2217967.6705489432252.866230232
#Sta/Elev= 30
       0 2124.86    63.7 2118.53    95.7 2116.89   171.8 2114.78   179.8 2114.03
   187.9 2112.09   200.5 2111.46   203.9 2110.34   211.9 2105.94   219.9 2104.28
   231.9 2099.87   235.9 2099.21     264 2098.29     296  2098.8   310.6 2097.71
   336.1  2097.2  365.852097.261   376.1 2098.76   396.2 2097.59   408.2  2099.3
   451.1 2098.33   516.4 2097.46   601.9 2098.37   751.1 2096.81   771.5 2096.31
   804.2 2097.83   808.8 2098.66   816.8  2102.4   832.8 2111.36   857.2  2116.1
#Mann= 8 ,-1,0
       0     .05       0   187.9    .016       0   200.5      .1       0
   310.6     .03       0   336.1    .045       0  365.85      .1       0
   451.1     .05       0   751.1      .1       0
#XS Ineff= 2 , 0
                          738.38         2106.29
Permanent Ineff=
       F       F
#Block Obstruct= 1 ,-1
  110.26  152.77 2136.51
Bank Sta=336.1,365.85
XS Rating Curve= 0 ,0
Exp/Cntr(USF)=0,0
Exp/Cntr=0.3,0.1

Type RM Length L Ch R = 1 ,381     ,263.1,263.1,263.1
XS GIS Cut Line= 4
2218048.01941825433163.1620262082218087.42891697432952.454039364
2218209.10124774432471.054817612 2218035.6640155432219.002918211
#Sta/Elev= 30
       0  2147.1      59 2134.86     120  2119.7   152.6 2113.67   160.7 2109.92
   173.2 2110.78   193.3 2109.32   197.3 2108.92   209.6 2102.97   250.7 2098.12
   260.5  2093.3   267.1 2092.66  285.66 2093.25   337.4 2096.23   374.5 2096.14
     391 2094.37   407.5 2096.04   419.9 2095.17   428.4 2096.51   507.5 2098.85
   646.8 2098.53   692.2  2096.4   737.5    2097   761.7 2095.63   832.5 2096.56
   849.1 2097.48     920 2096.38   936.5 2096.13   959.5  2097.9  1016.9 2114.06
#Mann= 7 ,-1,0
       0     .05       0   152.6    .016       0   193.3      .1       0
   260.5    .045       0  285.66      .1       0   832.5     .05       0
     920      .1       0
#XS Ineff= 2 , 0
                          590.87         2106.24
Permanent Ineff=
       F       F
Bank Sta=260.5,285.66
XS Rating Curve= 0 ,0
Exp/Cntr(USF)=0,0
Exp/Cntr=0.3,0.1