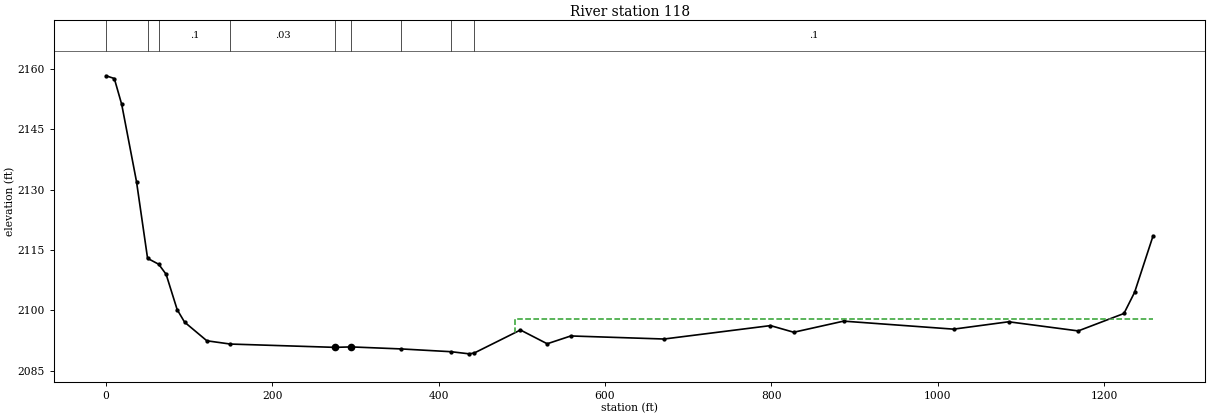
HEC-RAS study SWAGOCK.prj: SWAGOCK

--- SWAGOCK.g01 (geometry) --- (continued)

Type RM Length L Ch R = 1 ,118     ,,,
XS GIS Cut Line= 4
2218103.29922098433164.0580928812218327.24684429433054.729331897
2218309.61317316432386.4131962052218105.06258809432113.091293745
#Sta/Elev= 30
       0 2158.26     9.9 2157.58    18.8 2151.15    36.6 2131.98    49.9 2112.94
    63.3 2111.47    72.2 2108.98    85.5  2100.2    94.4  2097.1   121.2 2092.47
   149.4 2091.66   274.8 2090.84   294.8 2090.95   354.8 2090.45   414.8 2089.76
   436.7 2089.23   442.8 2089.44   498.3 2095.15   530.5 2091.73   558.9 2093.67
     671 2092.91     799 2096.24     827 2094.59     887 2097.35  1019.2 2095.36
  1085.4 2097.19  1169.1 2094.92  1224.1 2099.25  1236.9 2104.51  1259.1 2118.52
#Mann= 9 ,-1,0
       0      .1       0    49.9    .016       0    63.3      .1       0
   149.4     .03       0   274.8    .045       0   294.8     .03       0
   354.8      .1       0   414.8     .03       0   442.8      .1       0
#XS Ineff= 2 , 0
                          491.38         2097.99
Permanent Ineff=
       F       F
Bank Sta=274.8,294.8
XS Rating Curve= 0 ,0
Exp/Cntr(USF)=0,0
Exp/Cntr=0.3,0.1
LCMann Table=0

Chan Stop Cuts=-1
Use User Specified Reach Order=0
Composite Channel Slope=5